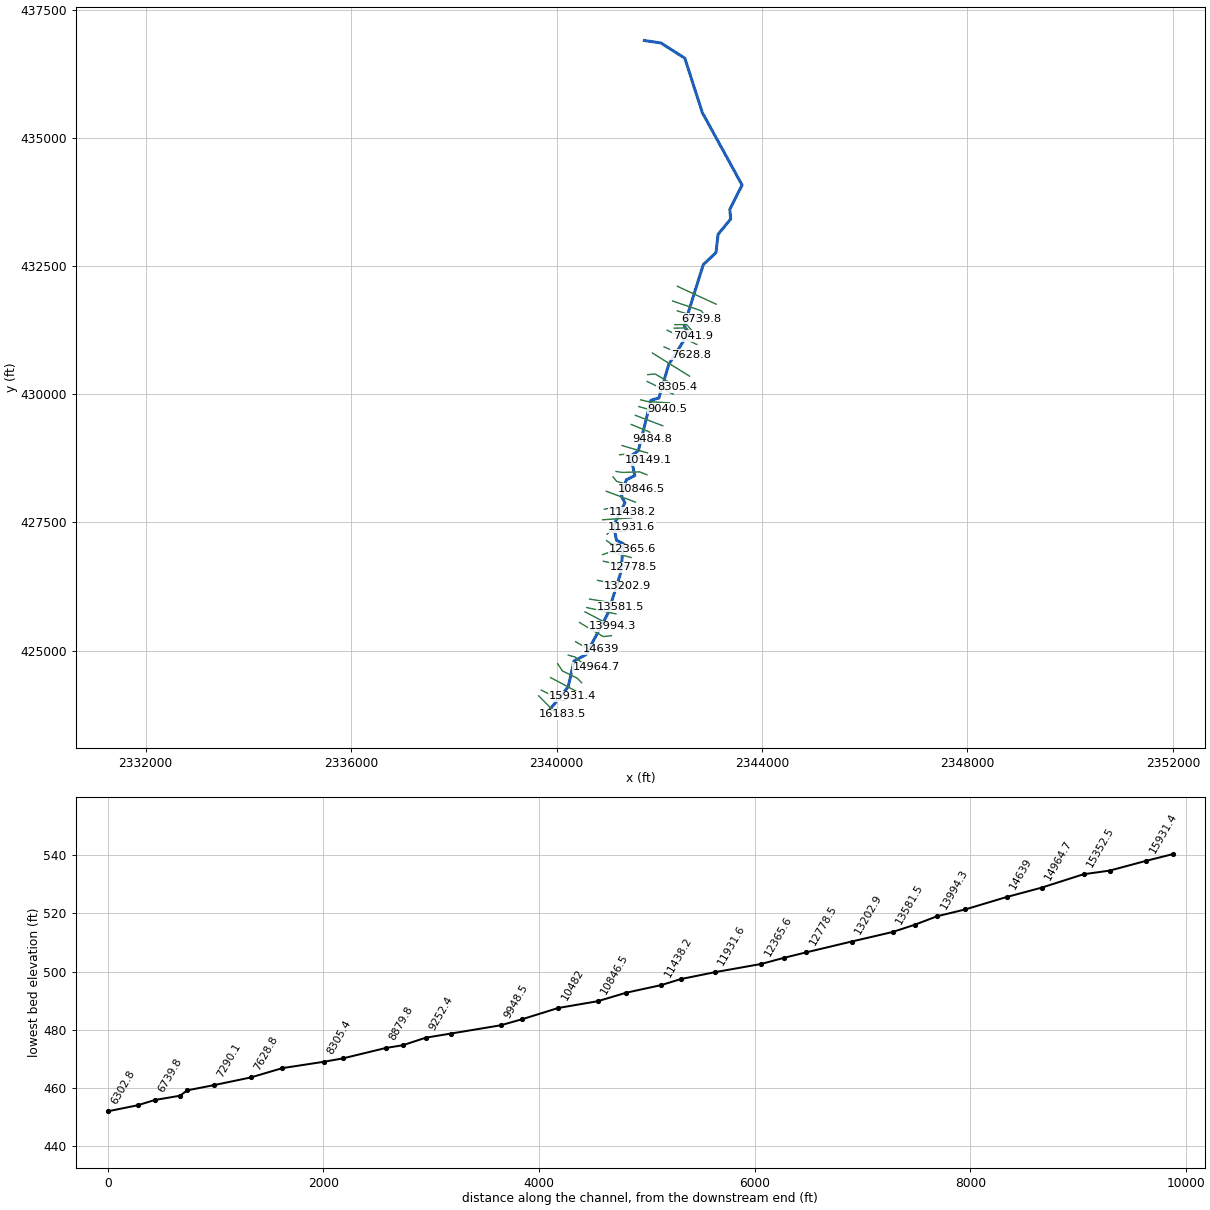
--- DRYRUN.prj (project) ---

Proj Title=DRYRUN
Current Plan=p01
Default Exp/Contr=0,0
English Units
Geom File=g01
Flow File=f01
Plan File=p01
BEGIN DESCRIPTION:
END DESCRIPTION:
DSS Export Rating Curves= 0
DSS Export Rating Curve Sorted= 0
DSS Export Volume Flow Curves= 0
DXF OffsetX= 0
DXF OffsetY= 0
DXF ScaleX= 0
DXF ScaleY= 0

--- DRYRUN.p01 (plan) ---

Plan Title=Floodplain
Program Version=4.00
Geom File=g01
Flow File=f01
K Sum by GR=0
Std Step Tol=0.01
Critical Tol=0.01
Num of Std Step Trials=20
Max Error Tol=0.3
Flow Tol Ratio=0.001
Split Flow NTrial=30
Split Flow Tol=0.02
Split Flow Ratio=0.02
Log Output Level=0
Friction Slope Method=1
Unsteady Friction Slope Method=2
Unsteady Bridges Friction Slope Method=1
Global Log Level=0
CheckData=False
Run HTab=0
Run UNet=0
Run PostProcess=0
UNET Theta=0
UNET Theta Warmup=0
UNET ZTol=0
UNET ZSATol=0
UNET MxIter=0
UNET MaxInSteps=0
UNET DtIC=0
UNET DtMin=0
UNET MaxCRTS=0
UNET WFStab=0
UNET SFStab=0
UNET WFX=0
UNET SFX=0
UNET DSS MLevel=0
UNET DZMax Abort=0
UNET Convert EG Bridges=0
UNET Use Existing IB Tables=0
UNET Froude Limit=0
UNET Froude Power=0
Write IC File=0
Echo Input=False
Echo Output=False
Write Detailed=0

--- DRYRUN.f01 (steady flow) ---

Flow Title=NFF Regression Equation
Program Version=4.00
Number of Profiles=1
Profile Names=P100yr
River Rch & RM=DRYRUN,Main      ,16183.5
518.3185
River Rch & RM=DRYRUN,Main      ,14964.7
564.4995
River Rch & RM=DRYRUN,Main      ,11931.6
763.3617
River Rch & RM=DRYRUN,Main      ,11931.6
610.1316
River Rch & RM=DRYRUN,Main      ,8879.8
812.3129
River Rch & RM=DRYRUN,Main      ,5669.6
900.2996
River Rch & RM=DRYRUN,Main      ,589.7
987.3124
River Rch & RM=DRYRUN,Main      ,229.4
988.9341
Boundary for River Rch & Prof#=DRYRUN,Main      ,1
Up Type=0
Dn Type=3
Dn Slope=0.008138

--- DRYRUN.g01 (geometry) ---

Geom Title=USGS 10m DEM
Program Version=4.10

River Reach=DRYRUN          ,Main
Reach XY= 30
     2339884.091      423870.313     2340227.873      424297.707
     2340340.892      424800.862     2340572.468      424921.727
     2341003.007       425731.51     2341252.559      426529.979
      2341301.16      427083.719     2341167.077      427155.035
     2341110.977      427442.093      2341331.32      427882.753
     2341263.649      428010.484     2341358.183      428331.744
      2341524.07      428416.341     2341442.361      428794.457
     2341593.559       428900.62      2341838.75      429883.889
     2341992.319      429926.127     2342186.249      430586.143
     2342555.774      431169.441     2342486.522      431344.271
     2342857.197      432527.397     2343103.969      432761.298
     2343145.314      433118.453     2343391.036      433417.188
     2343373.255      433603.532     2343612.704      434077.403
     2342838.116      435492.333     2342498.097      436551.475
     2342032.776      436849.024     2341709.916      436896.904

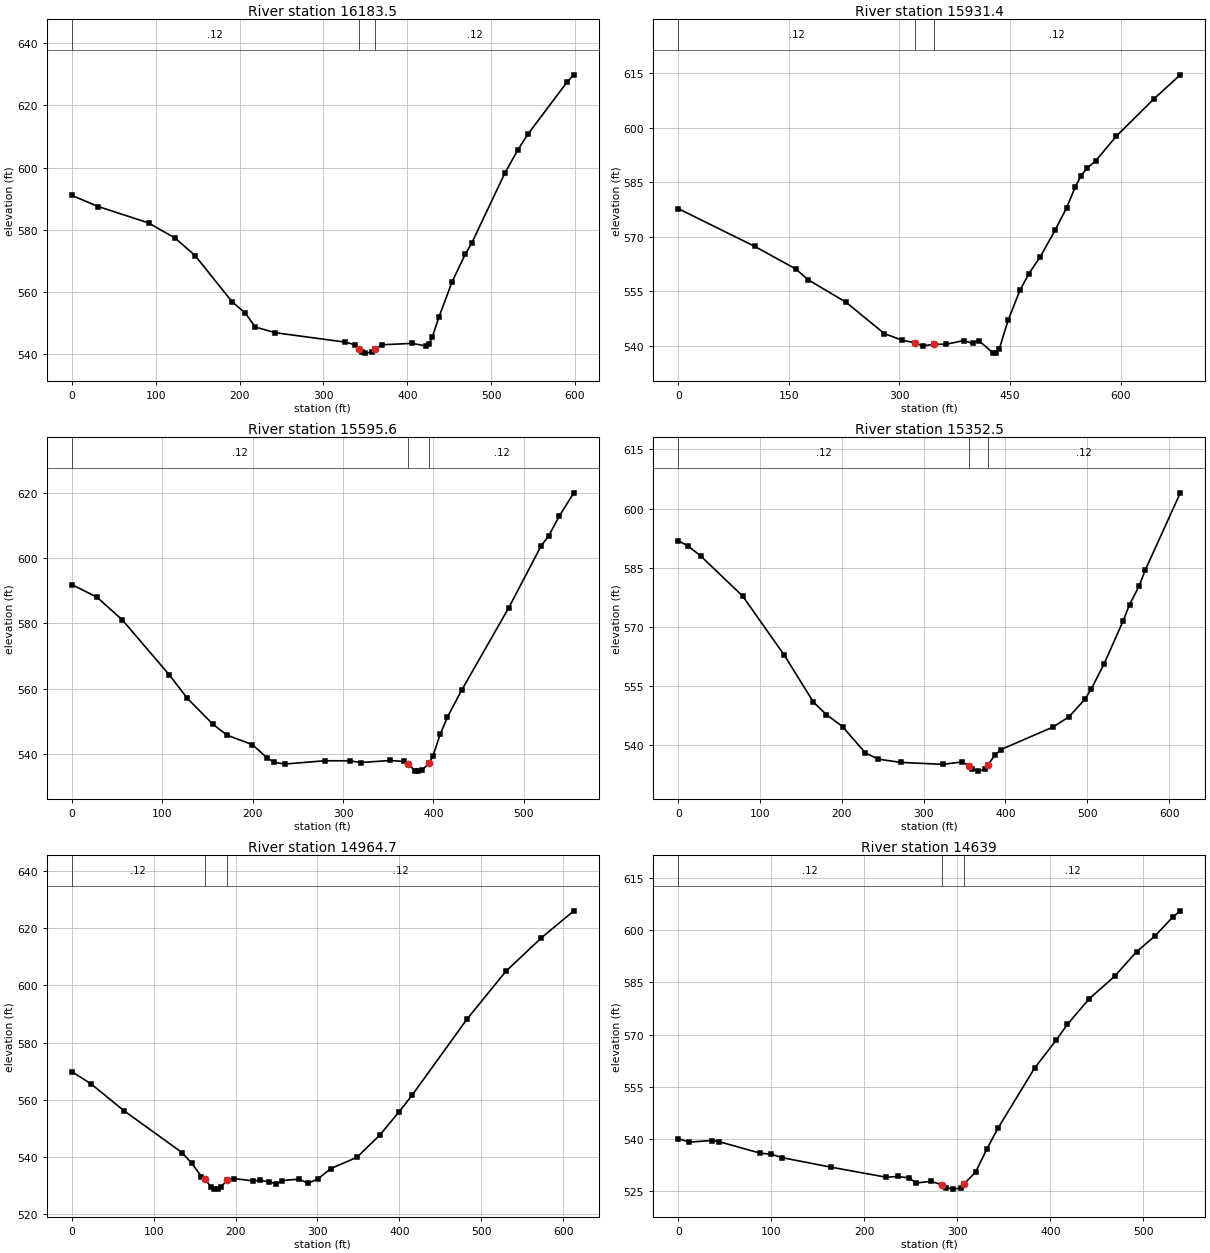
Type RM Length L Ch R = 1 ,16183.5 ,243.4,252.1,259.7
XS GIS Cut Line= 3
     2339651.887      424119.862     2339965.689      423803.455
     2340112.825      423761.789
#Sta/Elev= 30
       0  591.08    31.8  587.48    91.5  582.24   123.3  577.34   147.2  571.71
     191  556.94   206.9  553.27   218.8  548.78   242.7  546.96   326.3  543.92
   338.2  543.05   342.2  541.79   346.2  540.62   350.1   540.4   358.1   540.8
   362.1  541.86     370  543.09   405.8  543.53   421.8  542.73   425.7  543.25
   429.7  545.46   437.7  551.95   453.5  563.35   469.2   572.2     477  575.82
   516.2  598.15   531.9  605.75   543.6  610.66   590.7  627.56   598.6  629.82
#Mann= 3 ,-1 , 0
       0     .12       0   342.2    .045       0   362.1     .12       0
Bank Sta=342.2,362.1
XS Rating Curve= 0 ,0
Exp/Cntr=0.3,0.1

Type RM Length L Ch R = 1 ,15931.4 ,336,335.7,332.7
XS GIS Cut Line= 3
     2339701.367      424232.275     2340131.054      424020.035
     2340309.439      424113.785
#Sta/Elev= 30
       0  577.78   103.8  567.38   159.8  561.13   175.7  558.28   227.6  552.02
   279.6   543.4   303.5  541.61   320.6  540.91   331.5  540.04   347.4  540.49
   363.4  540.48   387.4  541.52   399.4   540.7   407.4   541.5   427.3  538.05
   431.3  538.12   435.3  539.19   447.3  547.06   463.3  555.28   475.2  559.81
   491.1   564.6   510.9  571.79   526.7  578.02   538.5  583.83   546.4  586.83
   554.3  588.89   566.2  590.92   593.8  597.64   645.2  607.96   680.8  614.55
#Mann= 3 ,-1 , 0
       0     .12       0   320.6    .045       0   347.4     .12       0
Bank Sta=320.6,347.4
XS Rating Curve= 0 ,0
Exp/Cntr=0.3,0.1

Type RM Length L Ch R = 1 ,15595.6 ,241.8,243.1,240
XS GIS Cut Line= 2
      2339884.96      424475.764     2340374.544      424214.046
#Sta/Elev= 30
       0  591.95      28  588.04    55.9  581.09   107.8  564.25   127.8  557.04
   155.8  549.16   171.7  545.74   199.7  542.84   215.7  538.84   223.7  537.41
   235.6  536.89   279.6  537.89   307.5  537.88   319.5  537.34   351.5  537.97
   367.4  537.69   371.4  537.03   379.4  534.86   383.4  534.71   387.4  535.08
   395.4  537.17   399.4  539.35   407.4  546.01   415.4  551.28   431.3  559.62
   483.3  584.86   519.2  603.88   527.2  606.76   539.2  612.98   555.2  620.07
#Mann= 3 ,-1 , 0
       0     .12       0   371.4    .045       0   395.4     .12       0
Bank Sta=371.4,395.4
XS Rating Curve= 0 ,0
Exp/Cntr=0.3,0.1

Type RM Length L Ch R = 1 ,15352.5 ,391.1,387.8,387.2
XS GIS Cut Line= 4
     2340021.679      424746.598     2340114.326      424605.076
     2340401.887      424464.046     2340489.127      424375.504
#Sta/Elev= 30
       0  591.87    11.8  590.53    27.5  587.98    78.7  577.82   129.8   562.8
   165.2  550.96     181   547.8   200.8  544.75   228.5  538.12   244.3   536.5
     272  535.67   323.4  535.18   347.1  535.79     355  534.84     359     534
   366.9  533.46   374.8  533.88   378.7  535.02   386.6  537.44   394.5  538.94
   457.8   544.6   477.6  547.22   497.2  551.69     505  554.33   520.5  560.62
   543.8  571.52   551.6  575.65   563.2   580.3     571  584.47   613.7  603.98
#Mann= 3 ,-1 , 0
       0     .12       0     355    .045       0   378.7     .12       0
Bank Sta=355,378.7
XS Rating Curve= 0 ,0
Exp/Cntr=0.3,0.1

Type RM Length L Ch R = 1 ,14964.7 ,318,325.7,325.8
XS GIS Cut Line= 4
     2340227.408      424914.566     2340364.127      424874.202
     2340569.781      424700.935     2340770.377      424680.191
#Sta/Elev= 30
       0   569.9    23.8  565.56    63.4  556.31   134.6  541.64   146.5  537.88
   158.4  533.22   162.3  532.39   170.2  529.64   174.2  528.86   178.1  528.86
   182.1   529.5     190  532.15   197.9  532.57   221.6  531.73   229.6   531.9
   241.4  531.45   249.3  530.62   257.2  531.85     277  532.34   288.9  530.91
   300.7  532.47   316.6  536.06   348.2  539.98   375.9  547.66   399.6  555.83
   415.4  561.59   482.6  588.22   530.1  604.94   573.6  616.67   613.1  626.06
#Mann= 3 ,-1 , 0
       0     .12       0   162.3    .045       0     190     .12       0
Bank Sta=162.3,190
XS Rating Curve= 0 ,0
Exp/Cntr=0.3,0.1

Type RM Length L Ch R = 1 ,14639   ,382.8,384.1,382.2
XS GIS Cut Line= 3
     2340373.242      425174.983     2340683.137      424992.691
     2340860.221      425025.244
#Sta/Elev= 30
       0  540.12      12  539.12      36  539.58    43.9  539.25    87.9  535.96
    99.9  535.63   111.9  534.65   163.8  531.95   223.7  529.04   235.7  529.26
   247.7  528.88   255.7  527.38   271.6  527.87   283.6  526.84   287.6  526.05
   295.6  525.63   303.6  525.97   307.6  527.22   319.6  530.52   331.6   537.1
   343.6  543.09     383  560.37   406.5  568.47   418.2  572.92   441.7  580.24
   469.1  586.73   492.6  593.75   512.2  598.24   531.8  603.78   539.6  605.49
#Mann= 3 ,-1 , 0
       0     .12       0   283.6    .045       0   307.6     .12       0
Bank Sta=283.6,307.6
XS Rating Curve= 0 ,0
Exp/Cntr=0.3,0.1

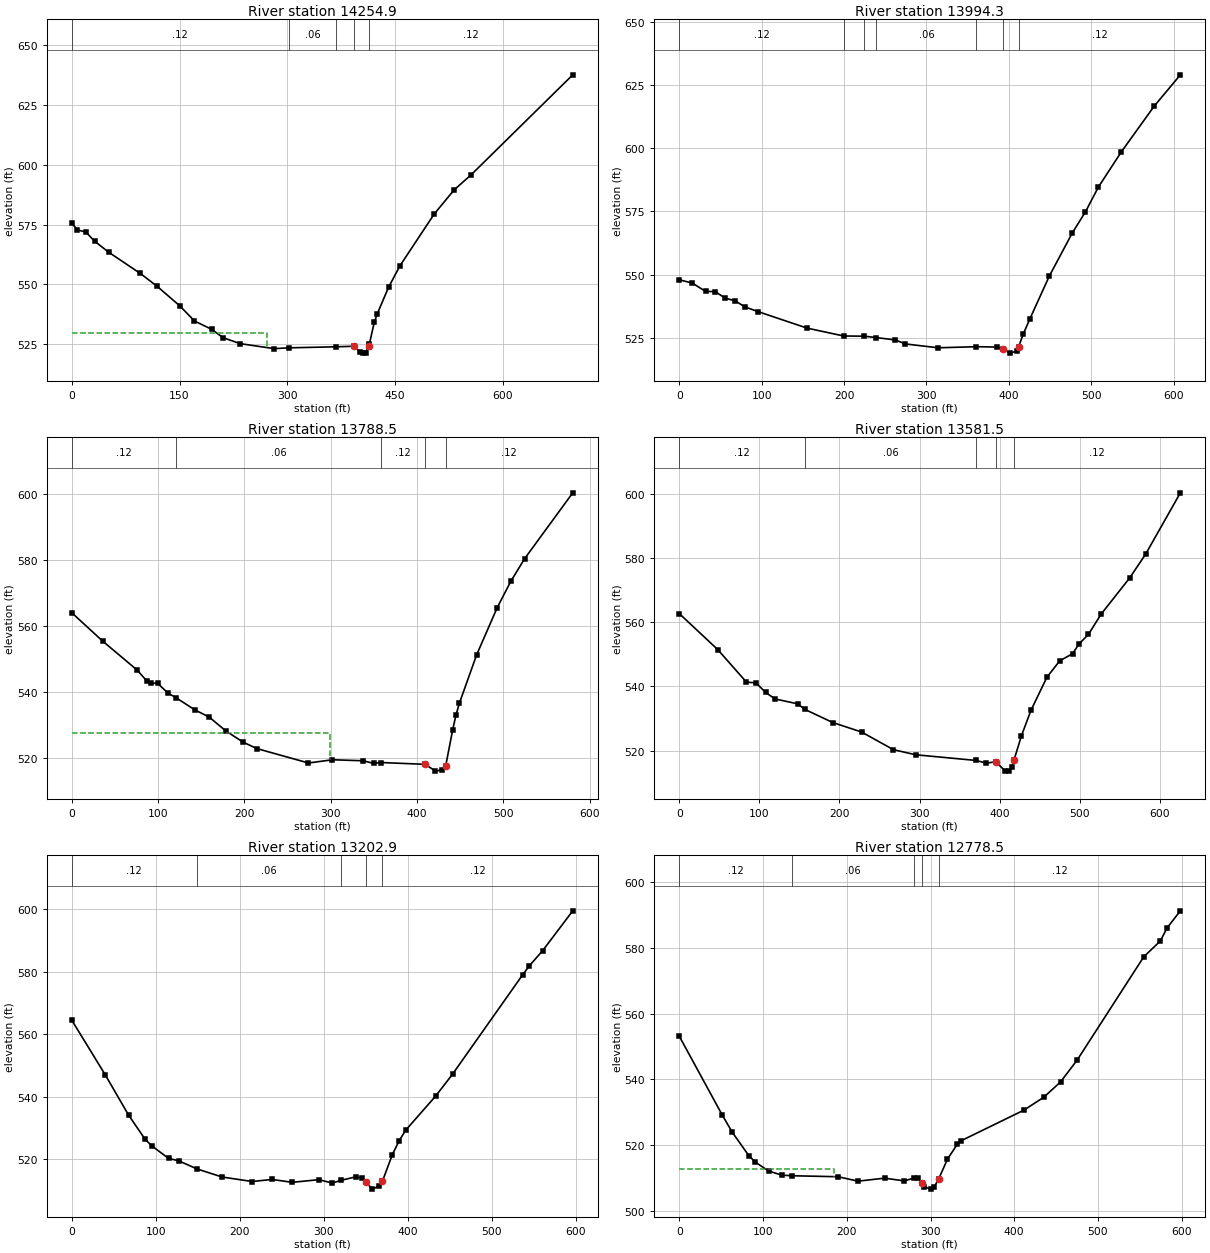
Type RM Length L Ch R = 1 ,14254.9 ,258.8,260.6,261.3
XS GIS Cut Line= 3
     2340447.563      425549.124     2340908.398      425275.244
     2341068.554      425292.171
#Sta/Elev= 30
       0   575.6     7.9   572.8    19.8  571.86    31.8  568.07    51.6  563.44
    95.3  554.64   119.1  549.18   150.9  540.94   170.8  534.77   194.6   531.3
   210.5  527.82   234.3  525.32   281.9  523.23  301.87523.5696   367.8524.0012
   393.1  524.24   401.1  521.71     405  521.36     409   521.4     413  523.72
  413.25  524.48   414.2  525.25   420.9  534.17   424.9  537.61   440.8  548.82
   456.7  557.83   504.3   579.4   532.1   589.5   555.7  595.77   697.1   637.5
#Mann= 5 ,-1 , 0
       0     .12       0  301.87     .06       0   367.8     .12       0
   393.1    .045       0  413.25     .12       0
#XS Ineff= 2 , 0
          271.37  529.64
Permanent Ineff=
       F       F
Bank Sta=393.1,413.25
XS Rating Curve= 0 ,0
Exp/Cntr=0.3,0.1

Type RM Length L Ch R = 1 ,13994.3 ,198.8,205.8,212.4
XS GIS Cut Line= 2
     2340554.792      425757.357     2341093.294      425474.462
#Sta/Elev= 30
       0  548.01    15.9  546.68    31.8  543.42    43.7  543.32    55.7  540.72
    67.6  539.73    79.5  537.31    95.4  535.44     155  528.91  199.46525.7952
   224.8525.7105     239525.1688   262.4  524.22   274.3  522.66   314.1  521.13
  360.78  521.56   385.6  521.42   393.3  520.51   401.6  519.02   409.5  519.83
  411.85  521.46   417.4  526.42   425.4  532.42   449.3  549.53   477.1  566.51
     493  574.82   508.9  584.71   536.7  598.58   576.5   616.6   608.3  628.99
#Mann= 7 ,-1 , 0
       0     .12       0  199.46     .06       0   224.8     .12       0
     239     .06       0  360.78     .12       0   393.3    .045       0
  411.85     .12       0
Bank Sta=393.3,411.85
XS Rating Curve= 0 ,0
Exp/Cntr=0.3,0.1

Type RM Length L Ch R = 1 ,13788.5 ,205,206.9,206.2
XS GIS Cut Line= 2
      2340588.74      425841.026     2341155.794      425717.952
#Sta/Elev= 30
       0  564.06    35.8  555.47    75.5  546.76    87.4  543.29    91.4  542.74
    99.4  542.71   111.3  539.78  121.24538.2579   143.1  534.57     159  532.52
   178.8  528.22   198.7  524.86   214.6  522.93   274.2  518.58     302  519.56
   337.8  519.25   349.7  518.46  357.63518.7277   409.4  518.18   421.3  516.12
   429.2  516.53   433.2  517.77   441.2  528.59   445.1  533.14   449.1  536.75
     469  551.33   492.8   565.6   508.7  573.62   524.6  580.42   580.3  600.33
#Mann= 5 ,-1 , 0
       0     .12       0  121.24     .06       0  357.63     .12       0
   409.4    .045       0   433.2     .12       0
#XS Ineff= 2 , 0
          298.84   527.7
Permanent Ineff=
       F       F
Bank Sta=409.4,433.2
XS Rating Curve= 0 ,0
Exp/Cntr=0.3,0.1

Type RM Length L Ch R = 1 ,13581.5 ,379.5,378.6,377.3
XS GIS Cut Line= 3
     2340643.376       426006.19     2341155.794      425923.681
     2341240.429      425858.577
#Sta/Elev= 30
       0  562.66    47.9  551.48    83.8  541.33    95.8  541.09   107.8   538.1
   119.8  536.07   147.7  534.58  156.73532.8478   191.6  528.75   227.6  525.79
   267.5  520.28   295.4   518.7  370.95516.9261   383.3  516.09   395.2  516.53
   407.2  513.61   411.2  513.65   415.2  515.03  417.89  516.94   427.2  524.56
   439.2  532.54   459.1  542.85   475.1  547.95   491.1  550.17   499.1  553.17
     511  556.21   526.9  562.52   562.5  573.78   582.3  581.14   625.8  600.28
#Mann= 5 ,-1 , 0
       0     .12       0  156.73     .06       0  370.95     .12       0
   395.2    .045       0  417.89     .12       0
Bank Sta=395.2,417.89
XS Rating Curve= 0 ,0
Exp/Cntr=0.3,0.1

Type RM Length L Ch R = 1 ,13202.9 ,422.5,424.5,423.6
XS GIS Cut Line= 2
     2340797.721      426371.598     2341382.356       426254.41
#Sta/Elev= 30
       0  564.54    39.8  547.05    67.6  534.12    87.4  526.31    95.4  524.19
   115.3   520.2   127.2  519.44  149.04516.8308   178.9  514.24   214.7  512.79
   238.5  513.45   262.4  512.53   294.2  513.38   310.1   512.3  320.17513.1501
   337.9  514.27   345.8  513.91   349.8  512.69   357.8  510.35   365.7  511.32
   369.7  512.81   381.6  521.42   389.6  525.82   397.5  529.25   433.3  540.24
   453.2  547.19   536.6  579.04   544.6  581.93   560.5  586.81   596.3  599.57
#Mann= 5 ,-1 , 0
       0     .12       0  149.04     .06       0  320.17     .12       0
   349.8    .045       0   369.7     .12       0
Bank Sta=349.8,369.7
XS Rating Curve= 0 ,0
Exp/Cntr=0.3,0.1

Type RM Length L Ch R = 1 ,12778.5 ,205.8,204.6,201.8
XS GIS Cut Line= 3
     2340913.606      426743.994     2341237.825      426672.379
     2341499.544        426622.9
#Sta/Elev= 30
       0   553.1    51.4  529.08    63.2  523.92      83  516.79    90.9  514.79
   106.7   512.1   122.5  510.85  134.51510.6719   189.7  510.37   213.4  509.02
   245.1  509.94   268.8   509.1  280.29509.9858   284.6  509.95   289.6  508.34
   292.5  507.34   300.4   506.6   304.4  507.32   309.6  509.59   320.2  515.71
     332  520.25     336  521.25   411.5  530.63   435.4  534.58   455.3  539.22
   475.2  545.89   554.7  577.29   574.5  582.11   582.5  586.07   598.4  591.28
#Mann= 5 ,-1 , 0
       0     .12       0  134.51     .06       0  280.29     .12       0
   289.6    .045       0   309.6     .12       0
#XS Ineff= 2 , 0
          184.85  512.63
Permanent Ineff=
       F       F
Bank Sta=289.6,309.6
XS Rating Curve= 0 ,0
Exp/Cntr=0.3,0.1

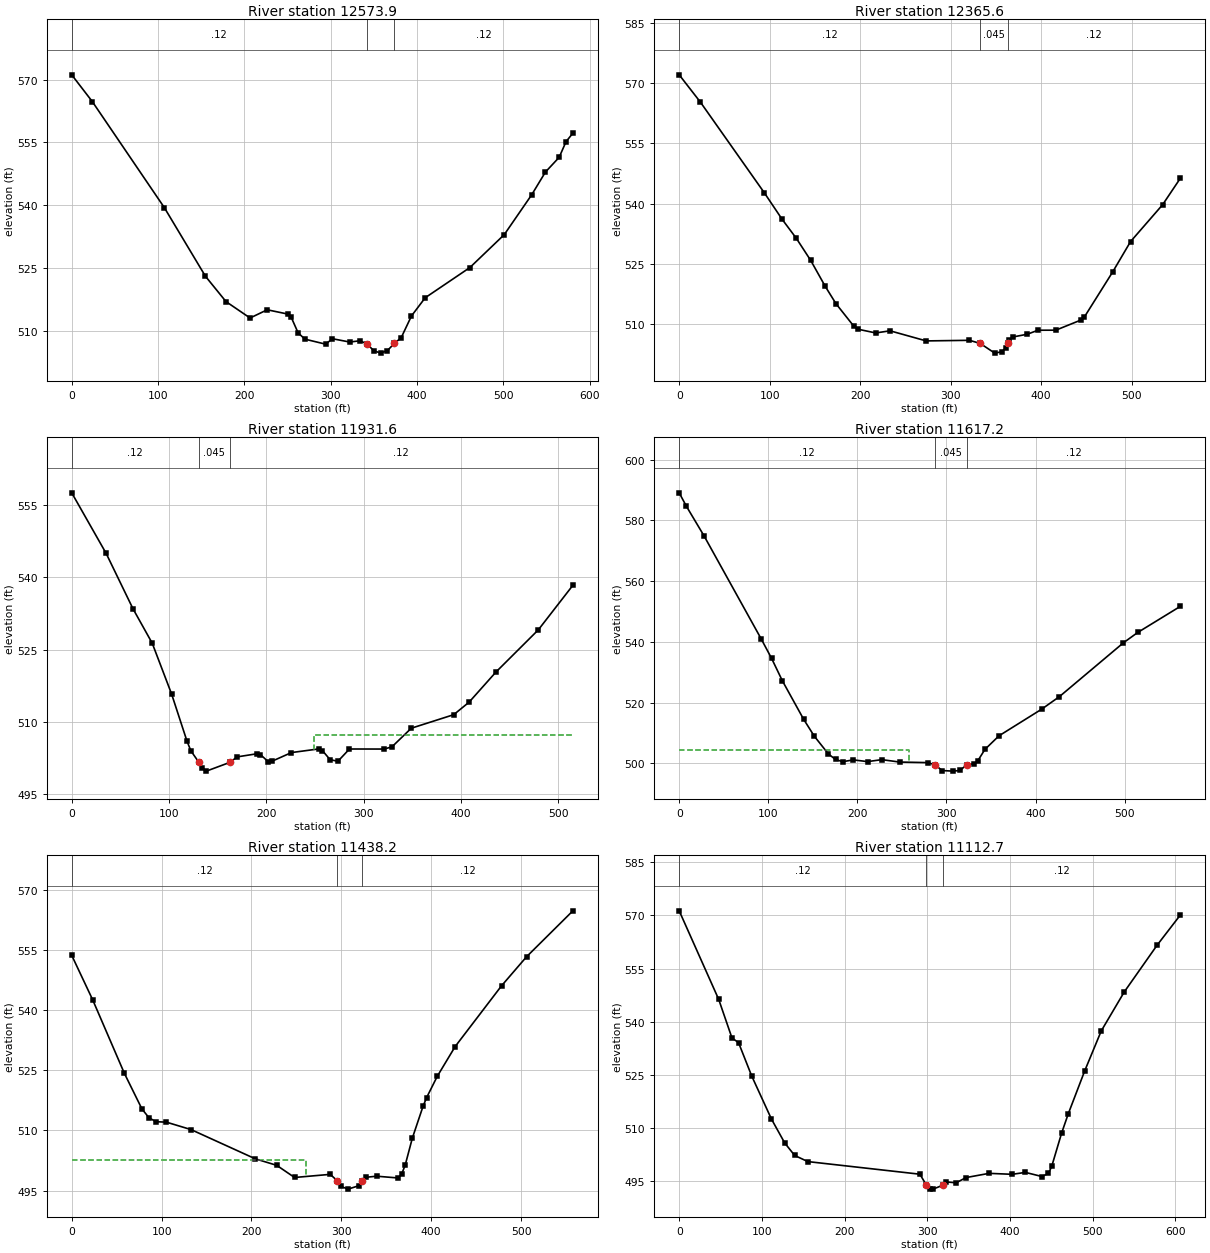
Type RM Length L Ch R = 1 ,12573.9 ,200.3,208.2,215.1
XS GIS Cut Line= 3
     2340896.679        426872.9     2341054.231      426927.587
     2341452.669      426815.608
#Sta/Elev= 30
       0  571.13    23.8  564.76   107.2  539.48   154.9  523.08   178.7  517.04
   206.6  513.12   226.5  515.08   250.3  514.06   254.3  513.28   262.3  509.57
   270.2  508.07   294.1  506.88   302.1  508.17     322  507.39   333.9  507.68
   341.9  506.98   349.8  505.34   357.8  504.74   365.8  505.36   373.7  507.05
   381.7  508.42   393.6  513.61   409.5  517.95   461.3  525.16   501.1  533.01
   532.9  542.52   548.8  547.94   564.7  551.45   572.7   555.2   580.6  557.21
#Mann= 3 ,-1 , 0
       0     .12       0   341.9    .045       0   373.7     .12       0
Bank Sta=341.9,373.7
XS Rating Curve= 0 ,0
Exp/Cntr=0.3,0.1

Type RM Length L Ch R = 1 ,12365.6 ,427.3,434.1,428.9
XS GIS Cut Line= 4
     2340973.502      427146.337     2341081.575      427068.212
     2341344.596      427073.421     2341470.898      426979.671
#Sta/Elev= 30
       0  572.14    23.5   565.3    94.1  542.67   113.7  536.07   129.4  531.32
   145.3   525.8   161.3  519.34   173.2     515   193.1  509.32   197.1  508.64
   217.1  507.69     233  508.22   272.9   505.7   320.7  505.85   332.6  505.07
   348.6  502.65   356.6     503   360.6  503.95  363.65  505.26   364.5  505.87
   368.5  506.68   384.5  507.36   396.4  508.37   416.1  508.38   443.6  510.89
   447.6  511.65     479  522.95   498.7  530.51   534.1  539.71   553.7  546.32
#Mann= 3 ,-1 , 0
       0     .12       0   332.6    .045       0  363.65     .12       0
Bank Sta=332.6,363.65
XS Rating Curve= 0 ,0
Exp/Cntr=0.3,0.1

Type RM Length L Ch R = 1 ,11931.6 ,312.9,314.4,315
XS GIS Cut Line= 4
     2340985.828      427271.439     2341035.298      427322.052
     2341333.051      427332.202     2341460.655      427403.383
#Sta/Elev= 30
       0  557.52    35.4  544.94    62.9  533.48    82.7  526.32   102.6  515.78
   118.4  506.01   122.4     504   130.4  501.68   134.3  500.38   138.3  499.79
   162.1  501.58   170.1  502.75   189.9  503.38   193.9  503.21   201.9  501.74
   205.8  501.85   225.7  503.64   253.5  504.39   257.5  504.05   265.4  502.17
   273.4  501.83   285.3  504.38     321  504.37     329  504.84   348.8  508.69
   392.4   511.5   408.2   514.1   435.8  520.35   479.3   529.1   514.8  538.34
#Mann= 3 ,-1 , 0
       0     .12       0   130.4    .045       0   162.1     .12       0
#XS Ineff= 2 , 0
                          248.78          507.23
Permanent Ineff=
       F       F
Bank Sta=130.4,162.1
XS Rating Curve= 0 ,0
Exp/Cntr=0.3,0.1

Type RM Length L Ch R = 1 ,11617.2 ,185.6,179,172.3
XS GIS Cut Line= 2
     2340899.283      427552.587     2341460.481      427590.348
#Sta/Elev= 30
       0  589.08       8  584.69    27.9   574.9    91.8   541.1   103.7  534.57
   115.7  527.24   139.6  514.55   151.6  508.96   167.5  503.08   175.5  501.27
   183.5  500.55   195.5  501.14   211.4  500.57   227.4  501.22   247.3  500.43
   279.2  500.24   287.2   499.5   295.2  497.63   307.2  497.44   315.1  497.66
   323.1  499.61   331.1   499.8   335.1  500.81   343.1  504.58     359  509.08
   406.9  517.85   426.8  521.98   498.6   539.7   514.6  543.09   562.5   551.7
#Mann= 3 ,-1 , 0
       0     .12       0   287.2    .045       0   323.1     .12       0
#XS Ineff= 2 , 0
          258.02  504.49
Permanent Ineff=
       F       F
Bank Sta=287.2,323.1
XS Rating Curve= 0 ,0
Exp/Cntr=0.3,0.1

Type RM Length L Ch R = 1 ,11438.2 ,326.5,325.5,318.7
XS GIS Cut Line= 3
     2340930.533      427758.316     2341060.742      427784.358
     2341477.408      427701.025
#Sta/Elev= 30
       0  553.63    23.4  542.51    58.6  524.23    78.1  515.38    85.9  513.18
    93.7  512.19   105.4  512.07   132.8  510.22   204.3  502.94   228.1  501.32
     248  498.29   287.7  499.07   295.6  497.45   299.6  496.06   307.5  495.39
   319.3  496.23   323.4  497.51   327.4  498.34   339.3  498.61   363.1  498.17
   367.1  499.11   371.1  501.38     379  508.06   390.9  515.99   394.9  518.18
   406.8   523.5   426.7  530.91   478.3  546.04   506.1  553.27   557.7  564.72
#Mann= 3 ,-1 , 0
       0     .12       0   295.6    .045       0   323.4     .12       0
#XS Ineff= 2 , 0
           261.1  502.55
Permanent Ineff=
       F       F
Bank Sta=295.6,323.4
XS Rating Curve= 0 ,0
Exp/Cntr=0.3,0.1

Type RM Length L Ch R = 1 ,11112.7 ,264.9,266.2,268.2
XS GIS Cut Line= 2
     2340969.596      428108.577     2341537.304      427896.337
#Sta/Elev= 30
       0  571.28    47.8  546.28    63.8  535.43    71.8  534.08    87.7  524.68
   111.6  512.52   127.6   505.8   139.6  502.28   155.5  500.54   291.1  496.98
     299  493.88     303  492.84     307  492.77     319  493.89     323  494.81
   334.9  494.55   346.9  496.03   374.8  497.22   402.7  496.95   418.7  497.49
   438.6  496.33   446.6  497.19   450.6  499.26   462.5  508.58   470.5  513.99
   490.4  526.12   510.4  537.39   538.3  548.42   578.2  561.66   606.1  570.11
#Mann= 3 ,-1 , 0
       0     .12       0     299    .045       0     319     .12       0
Bank Sta=299,319
XS Rating Curve= 0 ,0
Exp/Cntr=0.3,0.1

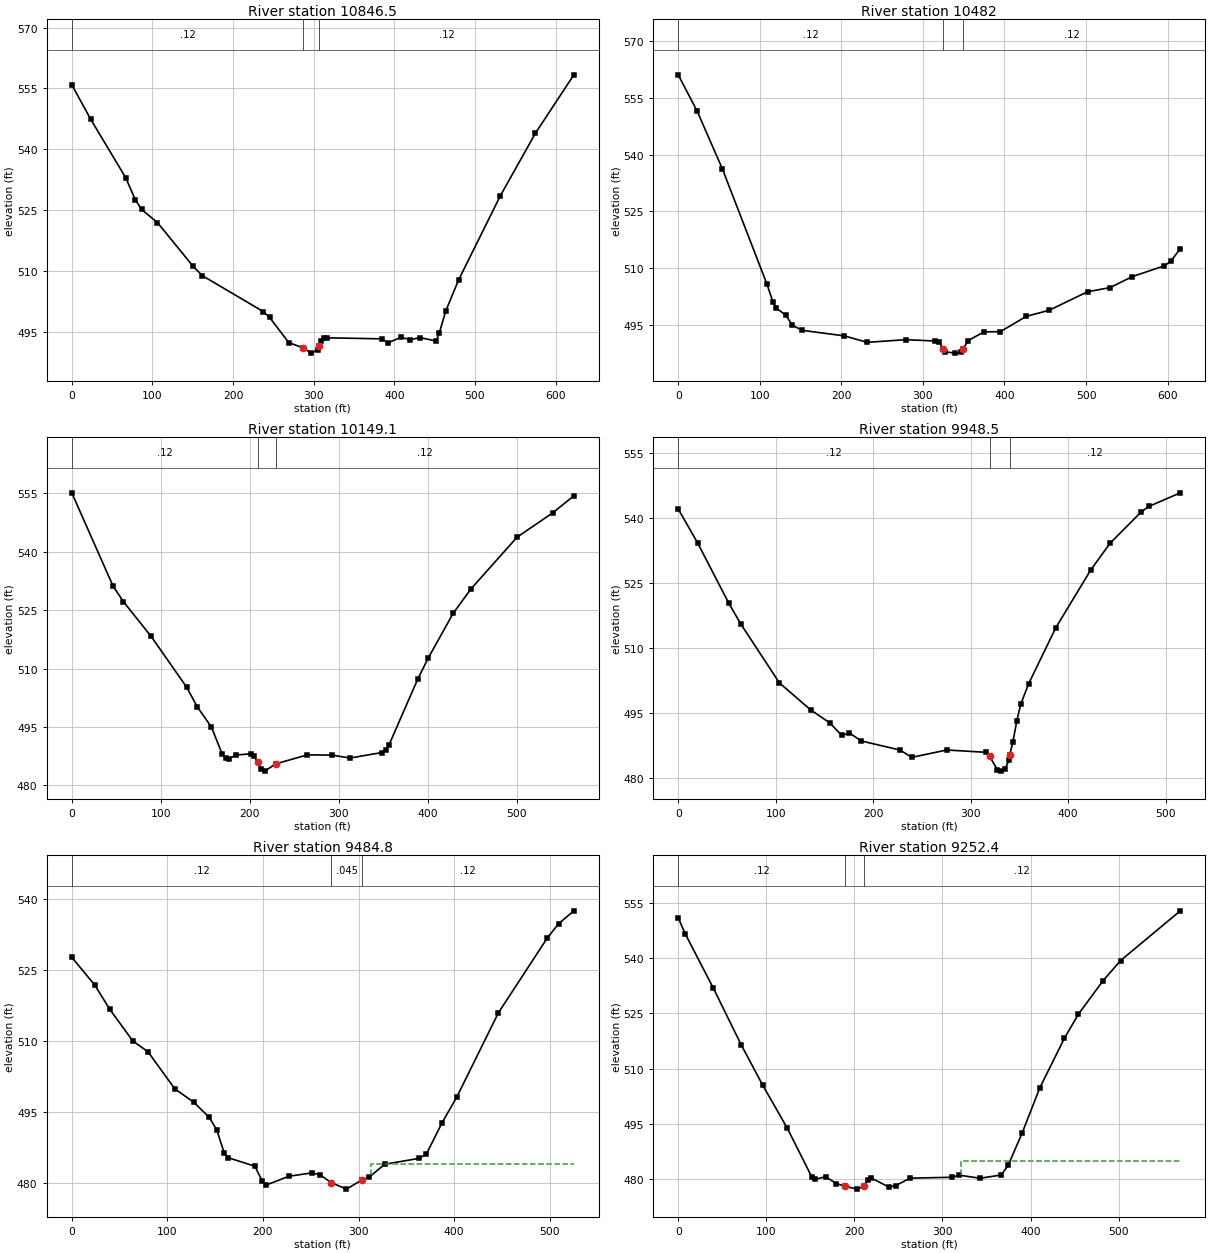
Type RM Length L Ch R = 1 ,10846.5 ,365.4,364.5,371.3
XS GIS Cut Line= 3
     2341101.106      428388.525     2341170.117      428302.587
       2341659.7      428151.546
#Sta/Elev= 30
       0  555.93    23.6  547.37    66.9  533.02    78.7  527.62    86.6   525.2
   106.3  521.97   149.9  511.34   161.8  508.92   237.3  500.08   245.3  498.62
   269.1  492.42   286.8  491.14   296.9  489.83   304.8   490.6   306.8  491.66
   308.8  492.73   312.8  493.54   316.8   493.6   384.3  493.35   392.2  492.38
   408.1  493.71     420  493.14   431.9  493.66   451.8   492.8   455.8  494.83
   463.7  500.18   479.6  507.82   531.2  528.48   574.9  543.96   622.6  558.36
#Mann= 3 ,-1 , 0
       0     .12       0   286.8    .045       0   306.8     .12       0
Bank Sta=286.8,306.8
XS Rating Curve= 0 ,0
Exp/Cntr=0.3,0.1

Type RM Length L Ch R = 1 ,10482   ,338.7,332.9,325.2
XS GIS Cut Line= 4
     2341158.398      428495.296     2341276.887      428475.764
     2341619.307      428485.836     2341761.262      428428.889
#Sta/Elev= 30
       0  561.06    23.2  551.46    54.2  536.17   108.5  505.89   116.2     501
   120.1  499.45     132  497.51     140  494.88     152  493.54   203.7  492.08
   231.6  490.37   279.4  491.08   315.3  490.71   319.3  490.57   325.1  488.63
   327.2  487.88   339.2  487.52   347.1   487.7  349.53  488.62   355.1   490.8
     375  493.14   394.9  493.19   426.8  497.24   454.7  498.84   501.9  503.74
   529.3  504.83   556.8  507.74     596  510.59   603.8  511.76   615.6  515.13
#Mann= 3 ,-1 , 0
       0     .12       0   325.1    .045       0  349.53     .12       0
Bank Sta=325.1,349.53
XS Rating Curve= 0 ,0
Exp/Cntr=0.3,0.1

Type RM Length L Ch R = 1 ,10149.1 ,200.1,200.6,197.9
XS GIS Cut Line= 3
      2341228.71      428819.514     2341313.346      428828.629
     2341779.492      428717.952
#Sta/Elev= 30
       0  555.08    46.4  531.15      58  527.18    89.1  518.27     129  505.25
     141   500.2     157  494.96     169   488.1     173  486.97     177  486.91
   184.9  487.82   200.9  488.12   204.9  487.55     209  485.91   212.9  484.14
   216.9  483.68     229  485.53   264.8  487.86   292.7  487.78   312.7  487.04
   348.6  488.45   352.6  489.03   356.6  490.46   388.6   507.2   400.5  512.66
   428.5  524.13   448.4  530.38   500.4   543.7   540.3  549.92   564.2  554.31
#Mann= 3 ,-1 , 0
       0     .12       0     209    .045       0     229     .12       0
Bank Sta=209,229
XS Rating Curve= 0 ,0
Exp/Cntr=0.3,0.1

Type RM Length L Ch R = 1 ,9948.5  ,469.4,463.7,457.7
XS GIS Cut Line= 2
     2341275.585      428999.202     2341770.377      428855.973
#Sta/Elev= 30
       0   542.1      20  534.22    51.9  520.34    63.9  515.64   103.8  501.95
   135.8  495.72   155.7  492.68   167.7  489.82   175.7  490.38   187.7  488.54
   227.6  486.44   239.6  484.75   275.5  486.45   315.4  485.92   319.4     485
   327.4  481.93   331.4  481.57   335.4  482.03   339.4  484.22  340.12  485.32
   343.4  488.41   347.4  493.23   351.4  497.02   359.4  501.72   387.3  514.66
   423.3  528.06   443.2  534.24   475.2  541.48   483.2  542.74   515.1  545.84
#Mann= 3 ,-1 , 0
       0     .12       0   319.4    .045       0  340.12     .12       0
Bank Sta=319.4,340.12
XS Rating Curve= 0 ,0
Exp/Cntr=0.3,0.1

Type RM Length L Ch R = 1 ,9484.8  ,228.2,232.5,232.9
XS GIS Cut Line= 3
     2341455.273       429410.66     2341809.439      429264.827
     2341869.335      429135.921
#Sta/Elev= 30
       0  527.77    23.9  521.93    39.9  516.72    63.8  510.07    79.8  507.76
   107.7  499.95   127.7  497.08   143.6  493.95   151.6  491.28   159.6  486.31
   163.6  485.37   191.5  483.57   199.5  480.34   203.5   479.6   227.4  481.46
   251.4  482.15   259.3  481.79   271.5   480.1   287.3  478.72   303.2  480.62
   311.2  481.25   327.2  483.97   363.1  485.22     371  486.14     387  492.64
   402.8  498.22   446.2  515.99   497.5  531.87   509.4  534.89   525.2  537.59
#Mann= 3 ,-1 , 0
       0     .12       0   271.5    .045       0   303.2     .12       0
#XS Ineff= 2 , 0
                          313.48          484.11
Permanent Ineff=
       F       F
Bank Sta=271.5,303.2
XS Rating Curve= 0 ,0
Exp/Cntr=0.3,0.1

Type RM Length L Ch R = 1 ,9252.4  ,208.6,211.8,213.2
XS GIS Cut Line= 2
       2341534.7      429589.046     2342067.252      429385.921
#Sta/Elev= 30
       0  550.98       8  546.61    39.9  531.86    71.8  516.34    95.7  505.62
   123.6  493.94   151.5  480.66   155.4  479.97   167.4  480.67   179.4  478.82
   189.5  478.07   203.3   477.3   211.2  478.18   215.2   479.9   219.2   480.3
   239.2  477.86   247.1  478.28   263.1  480.28   310.9  480.52   318.9  481.09
   342.8  480.25   366.7  481.15   374.7  483.82   390.6  492.64   410.5  504.81
   438.4  518.27   454.4  524.84   482.3  533.91   502.2  539.38     570  552.88
#Mann= 3 ,-1 , 0
       0     .12       0   189.5    .045       0   211.2     .12       0
#XS Ineff= 2 , 0
                          321.18          484.87
Permanent Ineff=
       F       F
Bank Sta=189.5,211.2
XS Rating Curve= 0 ,0
Exp/Cntr=0.3,0.1

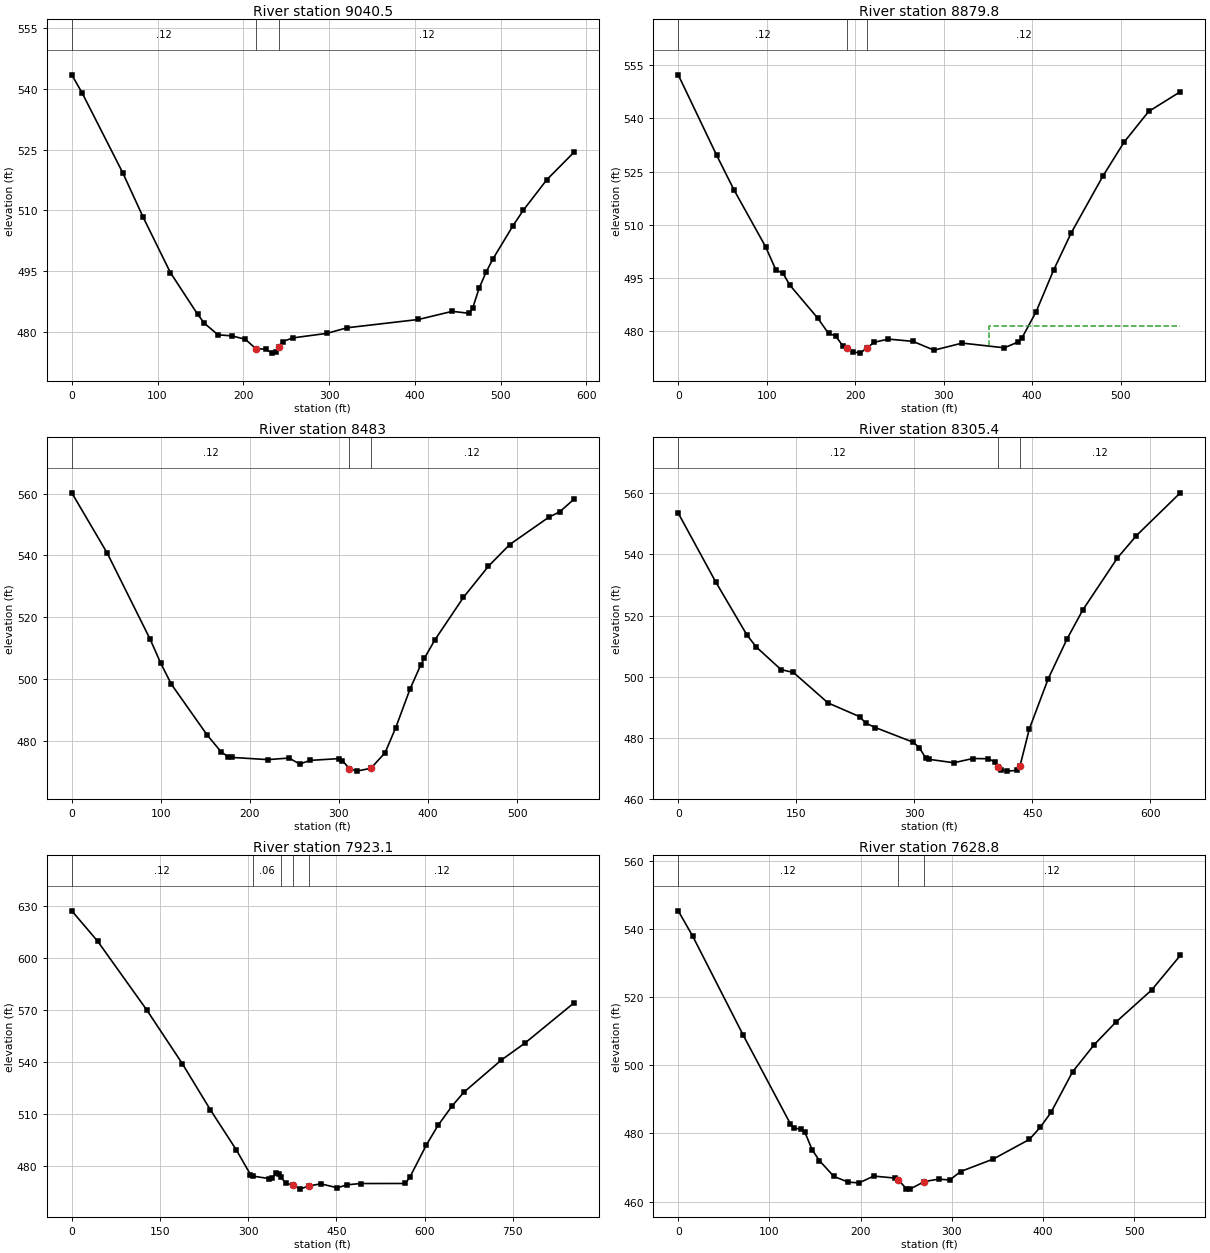
Type RM Length L Ch R = 1 ,9040.5  ,155.4,160.7,166.1
XS GIS Cut Line= 3
     2341602.408      429759.619     2341964.387      429655.452
     2342162.304      429721.858
#Sta/Elev= 30
       0  543.46    11.9  539.06    59.5  519.24    83.3  508.26     115   494.6
   146.7  484.33   154.6   482.1   170.5  479.24   186.4  478.99   202.2  478.16
   214.5  475.85     226  475.69   233.9  474.72   237.9  475.07   241.9  476.35
   245.8  477.57   257.7  478.48   297.4   479.6   321.2  480.99   404.2  483.03
   443.6  485.04   463.3  484.56   467.3  485.76   475.1  490.83     483  494.69
   490.9  497.93   514.5  506.21   526.4  509.99   553.9  517.56   585.4   524.3
#Mann= 3 ,-1 , 0
       0     .12       0   214.5    .045       0   241.9     .12       0
Bank Sta=214.5,241.9
XS Rating Curve= 0 ,0
Exp/Cntr=0.3,0.1

Type RM Length L Ch R = 1 ,8879.8  ,405.4,396.8,384.2
XS GIS Cut Line= 3
     2341637.564      429891.129     2341771.679      429858.577
     2342200.064      429831.233
#Sta/Elev= 30
       0  552.31    43.4  529.61    63.1  519.78    98.6  503.83   110.4  497.21
   118.3  496.28   126.2  492.92   157.9  483.54   169.8  479.31   177.8  478.63
   185.7  475.88   190.7  475.29   197.6  474.11   205.6  473.75   213.5  475.29
   221.5  476.82   237.4  477.71   265.2  477.07     289  474.58   320.8  476.58
   368.5  475.25   384.4  476.94   388.4  478.06   404.3  485.39   424.2  497.22
     444  507.67   479.8  523.71   503.7  533.28   531.5  541.96   567.3  547.54
#Mann= 3 ,-1 , 0
       0     .12       0   190.7    .045       0   213.5     .12       0
#XS Ineff= 2 , 0
                          351.22           481.3
Permanent Ineff=
       F       F
Bank Sta=190.7,213.5
XS Rating Curve= 0 ,0
Exp/Cntr=0.3,0.1

Type RM Length L Ch R = 1 ,8483    ,179.7,177.5,175.4
XS GIS Cut Line= 2
     2341765.169      430249.202     2342271.679      430001.806
#Sta/Elev= 30
       0  560.29      40  540.66      88  512.89     100  505.04   111.9  498.28
   151.9  481.91   167.9  476.35   175.9   474.8   179.9  474.62   219.9  473.91
   243.9  474.41   255.9  472.49   267.9  473.66   299.8  474.23   303.8  473.55
   311.8     471   319.8  470.18   335.8   471.1   351.8  476.15   363.8   484.3
   379.8  496.78   391.8  504.55   395.8  506.68   407.8  512.73   439.8  526.46
   467.8  536.52   491.7  543.55   535.7  552.41   547.7  554.11   563.7  558.18
#Mann= 3 ,-1 , 0
       0     .12       0   311.8    .045       0   335.8     .12       0
Bank Sta=311.8,335.8
XS Rating Curve= 0 ,0
Exp/Cntr=0.3,0.1

Type RM Length L Ch R = 1 ,8305.4  ,380.7,382.3,379
XS GIS Cut Line= 3
     2341774.283      430382.014     2341920.117      430395.035
     2342341.992      430142.431
#Sta/Elev= 30
       0  553.55    47.5  531.07    87.1  513.71    98.9  509.76   130.6  502.28
   146.4  501.35   190.4  491.36   230.4  486.88   238.4  484.74   250.4  483.31
   298.3  478.52   306.3  476.76   314.3  473.39   318.3   472.9   350.3  471.76
   374.3  473.15   394.3  473.08   402.3  472.05   406.3  470.47   410.3  469.35
   418.3  469.02   430.2  469.27   434.2  470.55   446.2  482.82   470.2  499.28
   494.2  512.35   514.2  521.84   558.2  538.87   582.2  546.16   638.1   560.2
#Mann= 3 ,-1 , 0
       0     .12       0   406.3    .045       0   434.2     .12       0
Bank Sta=406.3,434.2
XS Rating Curve= 0 ,0
Exp/Cntr=0.3,0.1

Type RM Length L Ch R = 1 ,7923.1  ,289.4,294.3,296.4
XS GIS Cut Line= 3
     2341865.423      430804.797      2342248.26      430565.215
     2342589.583      430352.966
#Sta/Elev= 30
       0  627.39      44  609.85   127.9     570   187.8   539.3   235.8  512.52
   279.8  489.46   303.8  475.26  307.77474.3591   335.7  472.92   339.7  473.22
   347.7   475.9   351.7  475.46  355.61 473.593   363.7  470.37   376.7  469.18
   387.7  466.85   403.7  468.74   423.6   469.9   451.6   467.6   467.5  469.34
   491.4  470.08     567  470.11     575  473.87   602.8  492.28   622.7  503.65
   646.6  514.81   666.5   522.7   730.2  541.28     770  550.96   853.6   574.2
#Mann= 5 ,-1 , 0
       0     .12       0  307.77     .06       0  355.61     .12       0
   376.7    .045       0   403.7     .12       0
Bank Sta=376.7,403.7
XS Rating Curve= 0 ,0
Exp/Cntr=0.3,0.1

Type RM Length L Ch R = 1 ,7628.8  ,337.7,338.7,336.7
XS GIS Cut Line= 3
     2342093.294      430923.681     2342452.669      430764.827
     2342610.221      430768.733
#Sta/Elev= 30
       0  545.29    15.9  537.83    71.4  508.73     123  482.78     127  481.55
   134.9   481.2   138.9   480.3   146.8  475.21   154.8  471.99   170.7  467.36
   186.5  465.68   198.4  465.48   214.3  467.47   238.1  466.87   241.5   466.3
     250   463.8     254  463.64   269.9  465.86   285.8  466.58   297.7  466.31
   309.6   468.8   345.3  472.45     385  478.22   396.9  481.78   408.7  486.13
   432.3  498.02     456  505.99   479.6  512.57     519  522.04   550.5  532.21
#Mann= 3 ,-1 , 0
       0     .12       0   241.5    .045       0   269.9     .12       0
Bank Sta=241.5,269.9
XS Rating Curve= 0 ,0
Exp/Cntr=0.3,0.1

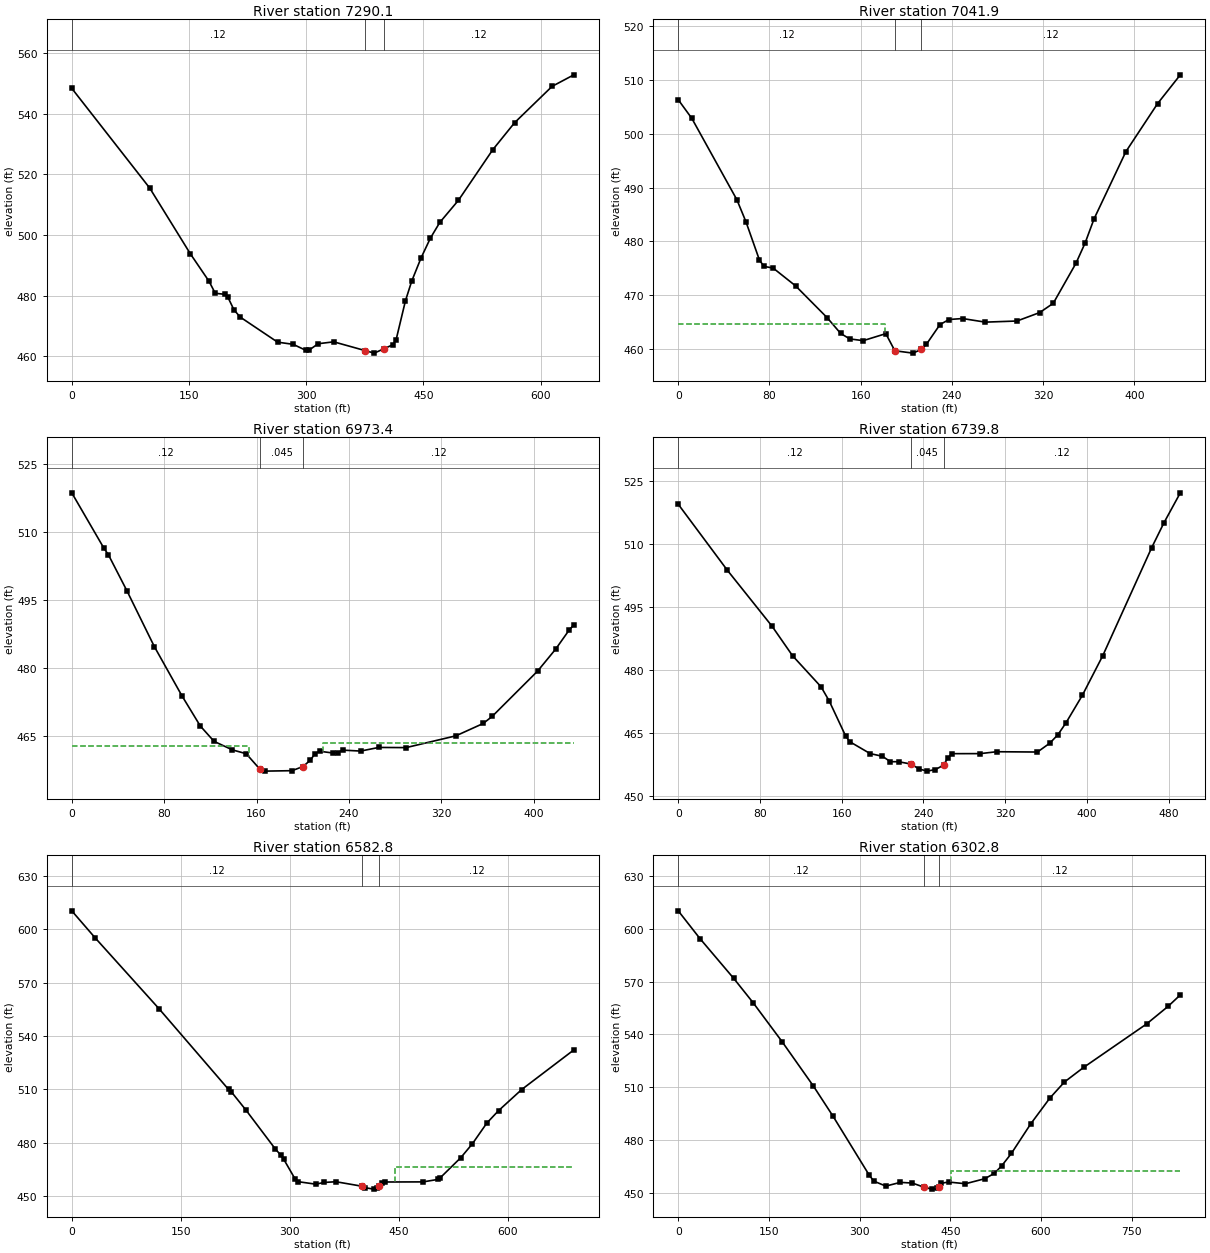
Type RM Length L Ch R = 1 ,7290.1  ,235,248.3,259.1
XS GIS Cut Line= 2
     2342151.337      431249.736     2342730.012      430970.556
#Sta/Elev= 30
       0  548.44    99.8   515.5   151.6  493.87   175.6  484.76   183.6  480.78
   195.5  480.45   199.5  479.62   207.5  475.34   215.5  472.93   263.4  464.64
   283.3  463.93   299.3  461.97   303.3  461.95   315.3  464.12   335.2  464.75
   375.1  461.88   387.1  461.02   399.1  462.42     411   463.8     415  465.38
     427   478.3     435  484.77     447  492.47   458.9  498.97   470.9  504.15
   494.8  511.47   538.7  528.16   566.7   537.1   614.6  549.08   642.5   552.9
#Mann= 3 ,-1 , 0
       0     .12       0   375.1    .045       0   399.1     .12       0
Bank Sta=375.1,399.1
XS Rating Curve= 0 ,0
Exp/Cntr=0.3,0.1

Type RM Length L Ch R = 1 ,7041.9  ,68.8,68.5,70.8
XS GIS Cut Line= 3
     2342290.342      431288.264     2342527.669      431294.543
     2342652.321      431134.619
#Sta/Elev= 30
       0  506.32    11.9  502.86    51.4  487.74    59.4  483.62    71.2  476.52
    75.2  475.33    83.1  475.05   102.9  471.72   130.6   465.8   142.4  462.88
   150.4  461.86   162.2  461.54     182  462.84   189.9  459.66   205.8  459.22
   213.2  459.92   217.6  460.87   229.5  464.53   237.4  465.47   249.3  465.65
   269.2  464.98     297  465.19   316.9  466.76   328.8  468.48   348.7  475.92
   356.7  479.67   364.6  484.19   392.5  496.68   420.3  505.61   440.2  510.95
#Mann= 3 ,-1 , 0
       0     .12       0   189.9    .045       0   213.2     .12       0
#XS Ineff= 2 , 0
          181.64  464.55
Permanent Ineff=
       F       F
Bank Sta=189.9,213.2
XS Rating Curve= 0 ,0
Exp/Cntr=0.3,0.1

Type RM Length L Ch R = 1 ,6973.4  ,241.2,233.6,221.1
XS GIS Cut Line= 3
     2342302.929      431357.275     2342533.398      431359.879
     2342664.908      431203.629
#Sta/Elev= 30
       0  518.69    27.8   506.5    31.8     505    47.7  497.13    71.5   484.8
    95.4  473.95   111.3   467.3   123.2  463.92   139.1  462.04     151   461.2
   162.9  457.78   166.9  457.36   190.7  457.46   200.2  458.37   206.6  459.78
   210.6  461.22   214.6  461.74   226.5  461.34   230.5  461.44   234.4  461.99
   250.1  461.78   265.8  462.58   289.4  462.54   332.6  465.14   356.2  467.86
     364  469.42   403.3   479.4     419  484.26   430.8  488.51   434.7  489.58
#Mann= 3 ,-1 , 0
       0     .12       0   162.9    .045       0   200.2     .12       0
#XS Ineff= 2 , 0
           153.4  462.95  217.59          463.66
Permanent Ineff=
       F       F
Bank Sta=162.9,200.2
XS Rating Curve= 0 ,0
Exp/Cntr=0.3,0.1

Type RM Length L Ch R = 1 ,6739.8  ,156.6,157,157.4
XS GIS Cut Line= 2
     2342353.189      431626.141     2342821.071      431475.967
#Sta/Elev= 30
       0  519.47    47.9   503.8    91.9  490.39   111.9  483.38   139.8  475.98
   147.8   472.6   163.8  464.29   167.8  462.92   187.8  460.08   199.8  459.44
   207.7  458.15   215.7  458.14   227.7  457.59   235.7  456.41   243.7   455.9
   251.7  456.28   259.7  457.32   263.7  458.98   267.7  460.06   295.6  460.07
   311.6  460.52   351.6  460.45   363.6  462.55   371.5  464.54   379.5   467.4
   395.5  473.95   415.5   483.4   463.4  509.14   475.4  515.06   491.4  522.19
#Mann= 3 ,-1 , 0
       0     .12       0   227.7    .045       0   259.7     .12       0
Bank Sta=227.7,259.7
XS Rating Curve= 0 ,0
Exp/Cntr=0.3,0.1

Type RM Length L Ch R = 1 ,6582.8  ,280.6,280,276.5
XS GIS Cut Line= 3
      2342259.96      431818.212      2342815.95      431628.108
     2342881.054      431547.379
#Sta/Elev= 30
       0  610.24      32  595.16   119.9  555.42   215.8  510.07   219.8  508.63
   239.8  498.47   279.8  476.87   287.8  473.16   291.8  470.89   307.8  459.57
   311.8  458.27   335.8  456.89   347.8  457.86   363.8  458.25   399.7  455.72
   403.7  454.91   415.7   454.1   419.7  454.49   423.7  455.83   427.7  457.55
   431.7   458.1   483.7  458.16   503.6  459.51   507.6  460.57   535.6  471.74
   551.6  479.54   571.6  491.23   587.6  498.12   619.5  509.98   691.3  532.21
#Mann= 3 ,-1 , 0
       0     .12       0   399.7    .045       0   423.7     .12       0
#XS Ineff= 2 , 0
                           445.7          466.63
Permanent Ineff=
       F       F
Bank Sta=399.7,423.7
XS Rating Curve= 0 ,0
Exp/Cntr=0.3,0.1

Type RM Length L Ch R = 1 ,6302.8  ,253.4,254.4,254.9
XS GIS Cut Line= 2
     2342352.762      432104.342     2343106.694      431756.512
#Sta/Elev= 30
       0  610.25    35.9  594.48    91.8  571.81   123.8  558.02   171.6  535.92
   223.5  510.62   255.5  493.73   315.4   460.2   323.3  456.56   343.3  453.72
   367.2  455.84   387.2  455.45   407.2     453   419.1     452   427.1  452.39
   431.1  453.43   435.1  455.34   447.1  456.04     475  455.06     507  457.93
   522.9     461   534.9  465.25   550.9  472.28   582.8  489.04   614.7  503.83
   638.7  512.92   670.6  521.26   774.4  545.89   810.3  555.99   830.3  562.44
#Mann= 3 ,-1 , 0
       0     .12       0   407.2    .045       0   431.1     .12       0
#XS Ineff= 2 , 0
                          451.86          462.04
Permanent Ineff=
       F       F
Bank Sta=407.2,431.1
XS Rating Curve= 0 ,0
Exp/Cntr=0.3,0.1