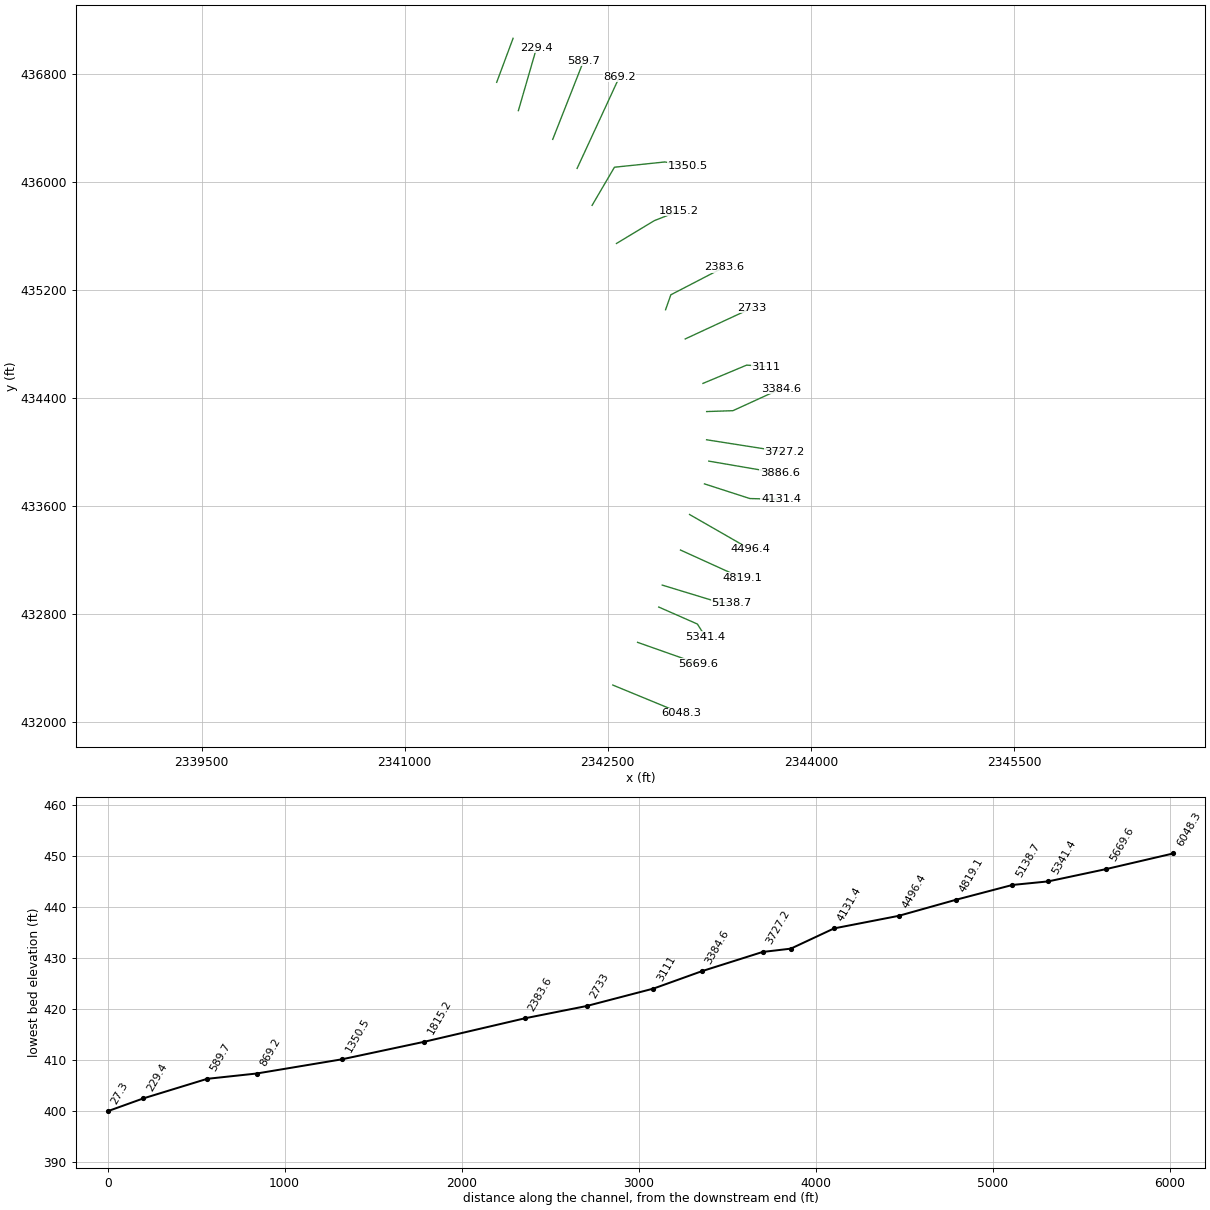
HEC-RAS study DRYRUN.prj: DRYRUN

--- DRYRUN.g01 (geometry) --- (continued)

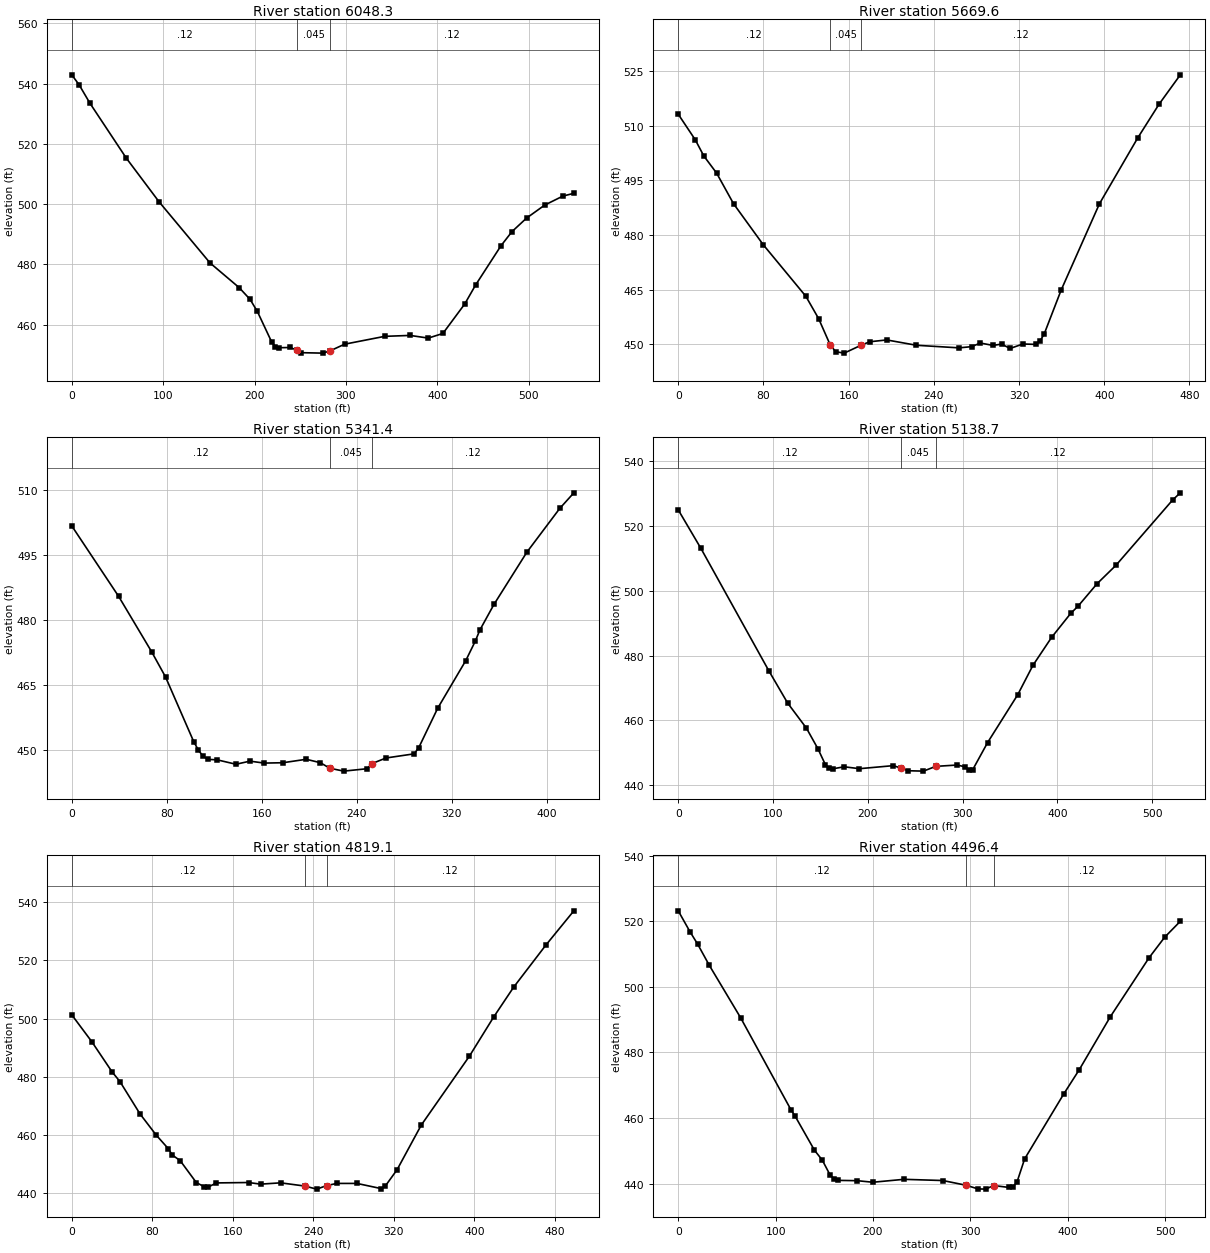
Type RM Length L Ch R = 1 ,6048.3  ,376.9,378.8,380.1
XS GIS Cut Line= 2
     2342536.783      432276.415     2343044.596       432066.78
#Sta/Elev= 30
       0  542.95       8  539.66    19.9  533.51    59.7  515.28    95.5   500.8
   151.3  480.49   183.1  472.32   195.1   468.4     203  464.43     219  454.08
   222.9  452.74   226.9  452.35   238.9  452.42   246.8   451.5   250.8   450.7
   274.7  450.55   282.6   451.3   298.6  453.52   342.4  456.12   370.2  456.43
   390.1  455.54   406.1  457.08     430  466.86   441.9  473.17   469.8  486.26
   481.7  490.89   497.6  495.37   517.5   499.7   537.4  502.69   549.4  503.61
#Mann= 3 ,-1 , 0
       0     .12       0   246.8    .045       0   282.6     .12       0
Bank Sta=246.8,282.6
XS Rating Curve= 0 ,0
Exp/Cntr=0.3,0.1

Type RM Length L Ch R = 1 ,5669.6  ,328.7,328.1,326.1
XS GIS Cut Line= 2
     2342719.943      432592.388     2343164.387       432435.27
#Sta/Elev= 30
       0  513.24      16   506.2      24  501.76      36  497.05    51.9  488.62
    79.9  477.29   119.8  463.14   131.8  456.99   142.6  449.81   147.8  447.88
   155.8  447.49   171.8  449.68   179.8  450.62   195.8  451.12   223.7  449.65
   263.7  448.94   275.6  449.28   283.6  450.27   295.6  449.61   303.6  449.98
   311.6  448.77   323.6  450.01   335.6  449.89   339.6  450.78   343.6  452.76
   359.5  464.83   395.5  488.61   431.4  506.71   451.4  515.98   471.4  524.08
#Mann= 3 ,-1 , 0
       0     .12       0   142.6    .045       0   171.8     .12       0
Bank Sta=142.6,171.8
XS Rating Curve= 0 ,0
Exp/Cntr=0.3,0.1

Type RM Length L Ch R = 1 ,5341.4  ,199.2,202.8,204.7
XS GIS Cut Line= 3
     2342876.193      432853.672     2343161.783      432727.804
     2343220.811      432634.054
#Sta/Elev= 30
       0  501.79    39.5  485.48    67.2  472.71      79  466.84   102.7   451.9
   106.7   449.9   110.6  448.52   114.6  447.79   122.5  447.68   138.3  446.66
   150.1  447.38     162  446.93   177.8  447.01   197.5  447.81   209.4  447.02
   217.3  445.74   229.1  445.07   248.9  445.63   252.8  446.81   264.7  448.11
   288.4  449.07   292.3  450.52   308.2  459.61   331.9  470.65   339.8  475.09
   343.8  477.74   355.6  483.62   383.3   495.7     411  505.82   422.9  509.44
#Mann= 3 ,-1 , 0
       0     .12       0   217.3    .045       0   252.8     .12       0
Bank Sta=217.3,252.8
XS Rating Curve= 0 ,0
Exp/Cntr=0.3,0.1

Type RM Length L Ch R = 1 ,5138.7  ,321.4,319.6,314.4
XS GIS Cut Line= 3
     2342902.235      433015.999     2343317.165      432889.263
     2343412.651       432881.45
#Sta/Elev= 30
       0  524.88    23.9  513.02    95.5  475.33   115.4  465.36   135.3  457.59
   147.3  451.31   155.2  446.39   159.2  445.23   163.2  445.09   175.1  445.71
   191.1  445.12   226.9  446.06   234.8  445.32   242.8  444.49   258.7  444.37
   271.7  445.84   294.5  446.25   302.5  445.69   306.5  444.76   310.5  444.72
   326.4  453.18   358.2  467.93   374.2  476.96     394  485.62     414  492.95
   421.9  495.23   441.8   502.1   461.8   507.8   521.7  527.96   529.7  530.13
#Mann= 3 ,-1 , 0
       0     .12       0   234.8    .045       0   271.7     .12       0
Bank Sta=234.8,271.7
XS Rating Curve= 0 ,0
Exp/Cntr=0.3,0.1

Type RM Length L Ch R = 1 ,4819.1  ,322.6,322.7,319.1
XS GIS Cut Line= 2
     2343036.783      433275.547     2343490.776       433068.95
#Sta/Elev= 30
       0  501.29      20  492.02    39.9  481.78    47.9  478.36    67.8  467.28
    83.8  460.05    95.8  455.38    99.8  453.19   107.7  451.24   123.7  443.73
   131.7  442.25   135.7  442.19   143.6  443.59   175.6  443.73   187.6  443.17
   207.5  443.62   231.4  442.52   243.4  441.46   253.2  442.68   263.4  443.42
   283.3  443.42   307.3  441.65   311.2  442.38   323.2  448.13   347.2  463.44
     395  487.08     419  500.46   438.9  510.74   470.9  525.18   498.8  536.99
#Mann= 3 ,-1 , 0
       0     .12       0   231.4    .045       0   253.2     .12       0
Bank Sta=231.4,253.2
XS Rating Curve= 0 ,0
Exp/Cntr=0.3,0.1

Type RM Length L Ch R = 1 ,4496.4  ,357,365,369.6
XS GIS Cut Line= 2
     2343103.623      433538.568     2343550.672      433281.624
#Sta/Elev= 30
       0  523.19      12  516.85      20     513      32  506.52      64  490.62
   115.9  462.44   119.9  460.64   139.9  450.18   147.9  447.18   155.9  442.65
   159.9  441.51   163.9  440.99   183.9  440.89   199.9  440.42   231.8  441.31
   271.8  440.94   295.8  439.49   307.8  438.39   315.8  438.32   323.8  439.42
   339.8  438.83   343.8  439.07   347.8   440.4   355.7  447.52   395.7  467.25
   411.7  474.68   443.7  490.88   483.6  508.92   499.6  515.16   515.6     520
#Mann= 3 ,-1 , 0
       0     .12       0   295.8    .045       0   323.8     .12       0
Bank Sta=295.8,323.8
XS Rating Curve= 0 ,0
Exp/Cntr=0.3,0.1

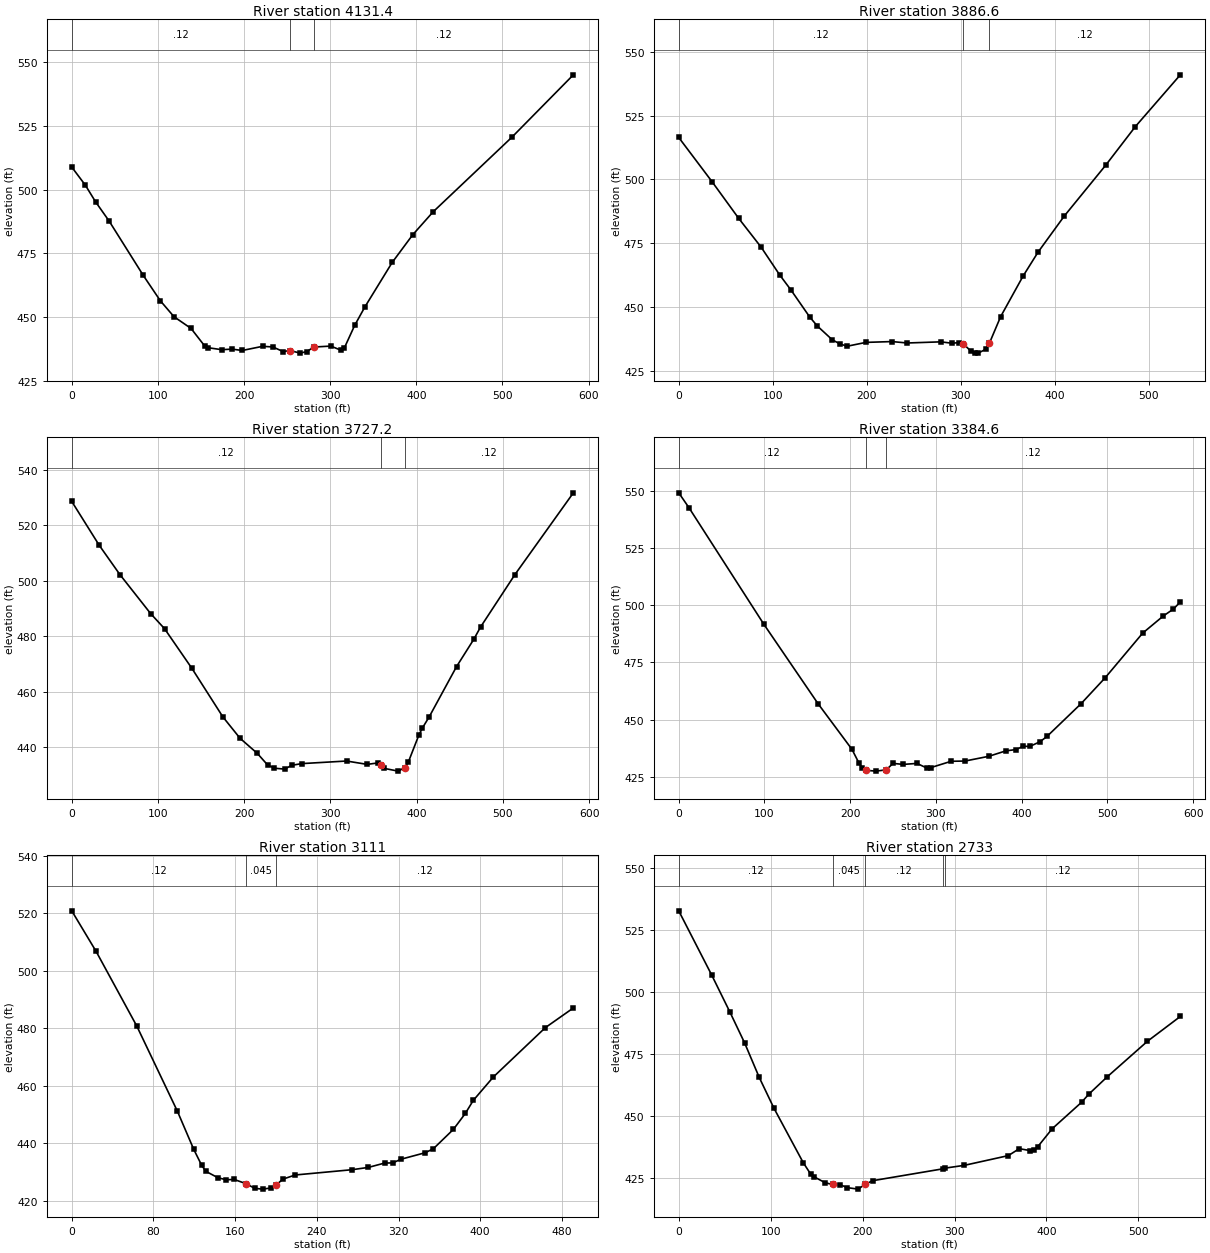
Type RM Length L Ch R = 1 ,4131.4  ,240.1,244.8,247.1
XS GIS Cut Line= 3
     2343213.867      433765.131     2343548.936      433656.624
     2343778.971      433650.547
#Sta/Elev= 30
       0  508.84    15.8  501.73    27.7  495.19    43.5  487.61    83.1  466.31
   102.9  456.37   118.7  450.14   138.5  445.54   154.3  438.68   158.3  437.98
   174.1  437.21     186  437.43   197.9   436.9   221.6  438.53   233.5  438.28
   245.4  436.46   253.3  436.89   265.1  435.86     273  436.48     281  438.25
   300.8  438.62   312.6  436.98   316.6     438   328.5  446.78   340.3  453.98
     372  471.43   395.8  482.27   419.6  491.31   510.9  520.53   582.3  545.02
#Mann= 3 ,-1 , 0
       0     .12       0   253.3    .045       0     281     .12       0
Bank Sta=253.3,281
XS Rating Curve= 0 ,0
Exp/Cntr=0.3,0.1

Type RM Length L Ch R = 1 ,3886.6  ,158.8,159.4,159.6
XS GIS Cut Line= 2
     2343245.985      433933.534     2343772.026      433843.256
#Sta/Elev= 30
       0   516.4    35.8   498.9    63.7  484.75    87.6  473.45   107.5  462.49
   119.5  456.59   139.4  446.03   147.4  442.54   163.3  437.14   171.3  435.53
   179.2  434.59   199.2   436.1     227  436.42     243  435.86   278.8  436.31
   290.8  435.77   298.7  436.03   302.7  435.55   310.7  432.74   314.7  432.03
   318.6  431.89   326.6   433.4   330.6  435.82   342.5  446.18   366.4   462.1
   382.4  471.51   410.3  485.65   454.1  505.44   485.9  520.69   533.7  540.95
#Mann= 3 ,-1 , 0
       0     .12       0   302.7    .045       0   330.6     .12       0
Bank Sta=302.7,330.6
XS Rating Curve= 0 ,0
Exp/Cntr=0.3,0.1

Type RM Length L Ch R = 1 ,3727.2  ,327.3,342.6,356.9
XS GIS Cut Line= 2
     2343229.492       434091.52     2343804.144      434001.242
#Sta/Elev= 30
       0  528.68    31.9  512.82    55.8  502.27    91.6  488.12   107.6  482.71
   139.4  468.34   175.3  450.82   195.2   443.1   215.2  437.65   227.1  433.48
   235.1  432.29     247  431.97     255  433.34   266.9  433.96   318.7  434.89
   342.6  433.68   354.6  434.18   358.6  433.36   362.6  432.22   378.5  431.24
   386.5  432.51   390.5  434.65   402.4  444.15   406.4   446.7   414.4  450.78
   446.2  468.98   466.2  478.85   474.1  483.31     514  502.28   581.7  531.79
#Mann= 3 ,-1 , 0
       0     .12       0   358.6    .045       0   386.5     .12       0
Bank Sta=358.6,386.5
XS Rating Curve= 0 ,0
Exp/Cntr=0.3,0.1

Type RM Length L Ch R = 1 ,3384.6  ,274.6,273.6,272.2
XS GIS Cut Line= 3
     2343229.926      434300.287     2343423.936      434306.797
     2343779.405      434469.558
#Sta/Elev= 30
       0  549.12    11.9  542.64      99  491.84   162.4  457.01   202.1  436.98
   210.1   431.1   214.1  428.81   218.1  427.85     230  427.48     242  428.04
     250  430.86   261.9  430.42   277.9  430.85   289.9  428.74   293.8  428.99
   317.8  431.79   333.8  431.88   361.7  433.96   381.6  436.34   393.6  436.91
   401.6  438.35   409.6  438.28   421.5  440.36   429.5  442.62   469.4  456.99
   497.3  468.23   541.2  487.81   565.1  495.25   577.1  498.35   585.1  501.44
#Mann= 3 ,-1 , 0
       0     .12       0   218.1    .045       0     242     .12       0
Bank Sta=218.1,242
XS Rating Curve= 0 ,0
Exp/Cntr=0.3,0.1

Type RM Length L Ch R = 1 ,3111    ,375.8,378,378.2
XS GIS Cut Line= 3
     2343202.582       434508.62     2343525.498      434644.037
     2343666.123       434633.62
#Sta/Elev= 30
       0  520.88    23.9  506.74    63.7  480.79   103.5  451.14   119.4  437.95
   127.3  432.31   131.3  430.27   143.2  428.02   151.2  427.34   159.2  427.42
   171.1  425.91   179.1  424.35     187  424.07     195  424.47   199.6  425.38
   206.9  427.56   218.8  428.99   274.6  430.83   290.5  431.63   306.4  433.14
   314.4   433.2   322.3  434.46   346.2  436.74   354.1  438.11   373.7  444.84
   385.4  450.39   393.2  454.93   412.8  463.06   463.8  480.25   491.2  487.09
#Mann= 3 ,-1 , 0
       0     .12       0   171.1    .045       0   199.6     .12       0
Bank Sta=171.1,199.6
XS Rating Curve= 0 ,0
Exp/Cntr=0.3,0.1

Type RM Length L Ch R = 1 ,2733    ,347.8,349.4,350.5
XS GIS Cut Line= 2
     2343071.505      434837.613     2343566.297      435067.648
#Sta/Elev= 30
       0  532.82    35.8  506.98    55.8  491.92    71.7  479.55    87.6  465.65
   103.6  453.24   135.4  431.33   143.4  426.78   147.4  425.58   159.3  423.22
   167.3  422.52   175.2  422.51   183.2  421.25   195.2  420.65   203.1  422.68
   211.1  424.06     287428.8115  289.99429.1329   310.7  430.24   358.5  434.16
   370.4  436.95   382.4  436.18   386.3  436.48   390.3  437.65   406.2  444.98
   438.1  455.63   446.1  458.94     466  465.89   509.8  480.24   545.6  490.25
#Mann= 5 ,-1 , 0
       0     .12       0   167.3    .045       0   203.1     .12       0
     287     .06       0  289.99     .12       0
Bank Sta=167.3,203.1
XS Rating Curve= 0 ,0
Exp/Cntr=0.3,0.1

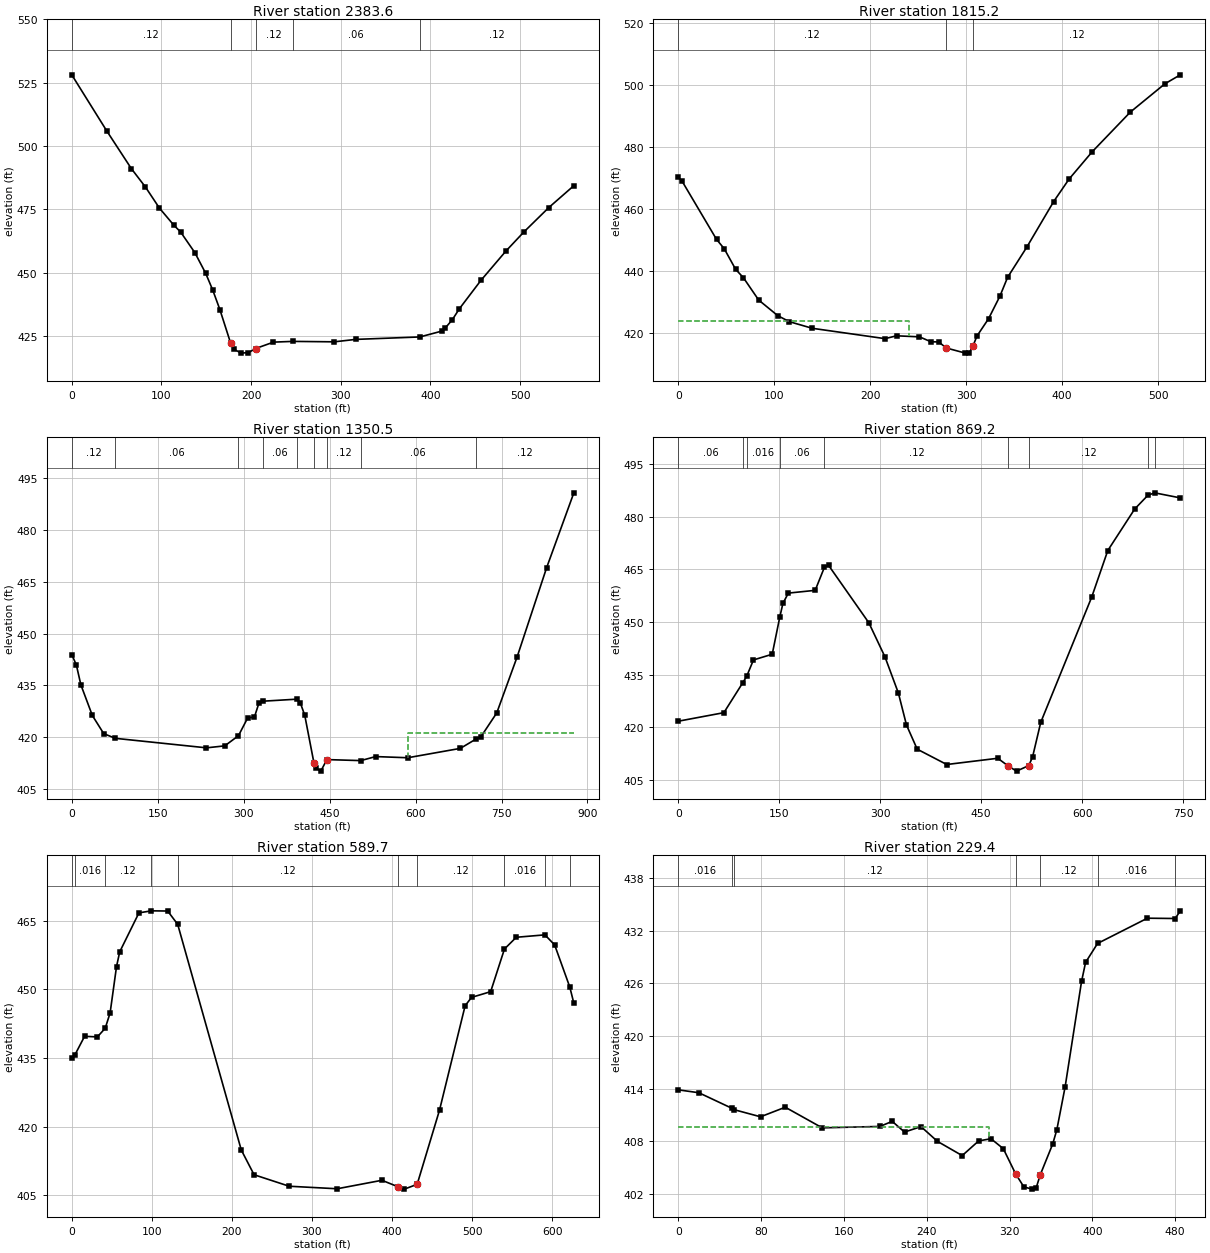
Type RM Length L Ch R = 1 ,2383.6  ,565.6,568.4,568.9
XS GIS Cut Line= 3
      2342926.54      435053.759     2342965.603      435164.436
     2343358.398      435368.429
#Sta/Elev= 30
       0  528.05    39.1  505.87    66.5  491.02    82.2  483.77    97.8  475.45
   113.5  468.86   121.4  466.03   137.3  457.88   149.3  449.78   157.2  443.16
   165.2  435.42   177.2  422.18   181.2  419.69   189.1  418.24   197.1  418.46
   205.1  420.06     225  422.58  246.44422.8696   292.8   422.7   316.7  423.66
  388.24424.6216   412.4   426.9   416.4  428.07   424.4   431.4   432.4  435.78
   456.3  446.92   484.2   458.5   504.2  466.02   532.1  475.69     560  484.31
#Mann= 5 ,-1 , 0
       0     .12       0   177.2    .045       0   205.1     .12       0
  246.44     .06       0  388.24     .12       0
Bank Sta=177.2,205.1
XS Rating Curve= 0 ,0
Exp/Cntr=0.3,0.1

Type RM Length L Ch R = 1 ,1815.2  ,475.4,464.7,453.3
XS GIS Cut Line= 3
     2342564.127      435544.211     2342844.075      435713.481
     2343026.367      435785.096
#Sta/Elev= 30
       0  470.35       4   469.1    39.9  450.32    47.9  447.32    59.8  440.66
    67.8     438    83.8  430.76   103.7  425.72   115.7  423.79   139.6  421.65
   215.4  418.31   227.4  419.23   251.3  418.89   263.3   417.3   271.3  417.25
   279.3  415.29   299.2  413.64   303.2  413.72   307.2  416.08   311.2  419.17
   323.2  424.71   335.1  432.03   343.1  438.09   363.1  447.83   391.1  462.54
   407.1  469.77   431.1  478.55     471   491.4     507  500.52     523   503.4
#Mann= 3 ,-1 , 0
       0     .12       0   279.3    .045       0   307.2     .12       0
#XS Ineff= 2 , 0
          240.31  424.03
Permanent Ineff=
       F       F
Bank Sta=279.3,307.2
XS Rating Curve= 0 ,0
Exp/Cntr=0.3,0.1

Type RM Length L Ch R = 1 ,1350.5  ,453.4,481.3,506.8
XS GIS Cut Line= 4
     2342384.005      435826.329     2342548.936      436108.447
       2342922.2      436147.509     2343093.641      436117.127
#Sta/Elev= 30
       0  443.93       8  440.92    15.9  435.17    35.9  426.31    55.8  421.05
   76.14419.6968   235.1  416.95     267  417.52   290.9  420.46   306.9  425.58
   318.8  425.88   326.8  429.99  333.06430.4373  392.53431.0276   398.7  430.03
   406.6  426.36   422.6   412.6   426.6  411.07   434.6  410.21   445.2  413.55
   504.3 413.255   530.4  414.42   586.3  414.08   678.1  416.79  704.59419.4043
     714  420.15   741.7  427.06   777.3   443.3   828.7  469.07   876.2  490.73
#Mann= 9 ,-1 , 0
       0     .12       0   76.14     .06       0   290.9    .016       0
  333.06     .06       0  392.53     .12       0   422.6    .045       0
   445.2     .12       0   504.3     .06       0  704.59     .12       0
#XS Ineff= 2 , 0
                          586.65           421.3
Permanent Ineff=
       F       F
Bank Sta=422.6,445.2
XS Rating Curve= 0 ,0
Exp/Cntr=0.3,0.1

Type RM Length L Ch R = 1 ,869.2   ,279.1,279.5,280.9
XS GIS Cut Line= 2
     2342273.328      436099.766     2342585.828      436776.849
#Sta/Elev= 30
       0  421.68    67.8  424.12   95.47432.5458  101.61434.4745   111.7  439.17
   139.6   440.8  150.72 451.326   155.5  455.32   163.5  458.25   203.4  459.04
  217.17465.6464   223.3  466.17   283.1  449.78   307.1  440.02     327   429.7
     339   420.6   354.9   413.7   398.8  409.32   474.6   411.1   490.5  408.84
   502.5  407.43   520.8  409.03   526.4  411.59   538.4  421.35   614.1  457.11
     638  470.41   677.9  482.24  697.52486.1702  707.51 486.876   745.7  485.43
#Mann= 9 ,-1 , 0
       0     .06       0   95.47     .12       0  101.61    .016       0
  150.72     .06       0  217.17     .12       0   490.5    .045       0
   520.8     .12       0  697.52     .08       0  707.51    .016       0
Bank Sta=490.5,520.8
XS Rating Curve= 0 ,0
Exp/Cntr=0.3,0.1

Type RM Length L Ch R = 1 ,589.7   ,357.2,360.3,361.1
XS GIS Cut Line= 2
     2342093.207       436314.61      2342322.59      436898.233
#Sta/Elev= 30
       0     435    3.57435.5801      16  439.74      32  439.62   41.77441.5036
    47.9  444.86    55.9  454.98    59.9  458.19    83.9  466.69   99.58467.1338
   119.8  467.09   132.3464.1837   211.7  414.94   227.7  409.53   271.6  407.02
   331.5  406.47   387.4  408.32   407.4  406.91   415.4  406.39   431.4  407.44
   459.3  423.62   491.3  446.41   499.3  448.24   523.2  449.49  540.43458.8036
   555.2  461.36  590.95461.8891   603.1   459.7  622.09450.4708   627.1  446.96
#Mann= 10 ,-1 , 0
       0     .12       0    3.57    .016       0   41.77     .12       0
   99.58     .08       0   132.3     .12       0   407.4    .045       0
   431.4     .12       0  540.43    .016       0  590.95     .08       0
  622.09     .12       0
Bank Sta=407.4,431.4
XS Rating Curve= 0 ,0
Exp/Cntr=0.3,0.1

Type RM Length L Ch R = 1 ,229.4   ,203.7,202.1,200.8
XS GIS Cut Line= 2
     2341839.518      436527.139     2341974.283      436992.995
#Sta/Elev= 30
       0  413.87    19.9  413.54   51.94411.7628   54.14411.6048    79.5   410.8
   103.4  411.89   139.1  409.54   194.8   409.7   206.7  410.28   218.6  409.06
   234.5  409.68   250.4     408   274.3  406.38   290.2  408.05   302.1   408.3
     314  407.17     326  404.28   333.9  402.81   341.9  402.56   345.8  402.72
   349.8  404.22   361.7  407.69   365.7  409.31   373.7  414.19   389.6  426.22
   393.5  428.39  405.07430.5444   453.2  433.42  480.09433.3855     485  434.26
#Mann= 7 ,-1 , 0
       0    .016       0   51.94     .08       0   54.14     .12       0
     326    .045       0   349.8     .12       0  405.07    .016       0
  480.09     .12       0
#XS Ineff= 2 , 0
          300.39  409.69
Permanent Ineff=
       F       F
Bank Sta=326,349.8
XS Rating Curve= 0 ,0
Exp/Cntr=0.3,0.1

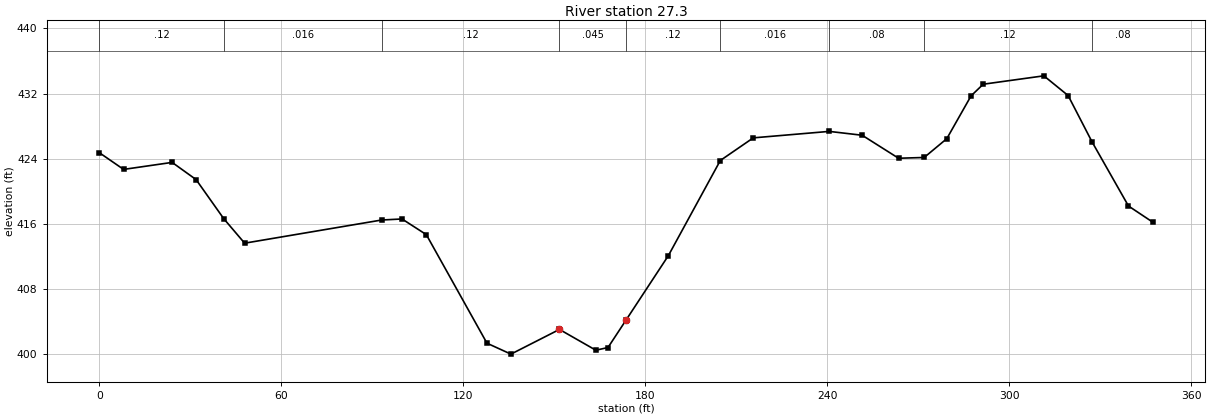
Type RM Length L Ch R = 1 ,27.3    ,24.5,27.3,30.2
XS GIS Cut Line= 2
     2341679.361      436736.774     2341800.455      437062.295
#Sta/Elev= 30
       0  424.75       8   422.7      24  423.56    31.9  421.45   41.01416.6606
    47.9  413.65   93.09416.4929    99.8  416.62   107.8   414.7   127.8  401.38
   135.7  400.04   151.7  403.07   163.7  400.52   167.7  400.85   173.6  404.19
   187.6  412.12  204.73423.7924   215.6  426.57  240.64427.3629   251.5  426.89
   263.5  424.07  271.94424.1626   279.4  426.47   287.4  431.72   291.4  433.15
   311.4  434.18   319.4  431.76  327.28426.0818   339.3  418.21   347.3  416.23
#Mann= 9 ,-1 , 0
       0     .12       0   41.01    .016       0   93.09     .12       0
   151.7    .045       0   173.6     .12       0  204.73    .016       0
  240.64     .08       0  271.94     .12       0  327.28     .08       0
Bank Sta=151.7,173.6
XS Rating Curve= 0 ,0
Exp/Cntr=0.3,0.1

Chan Stop Cuts=-1
Use User Specified Reach Order=0
Composite Channel Slope=5